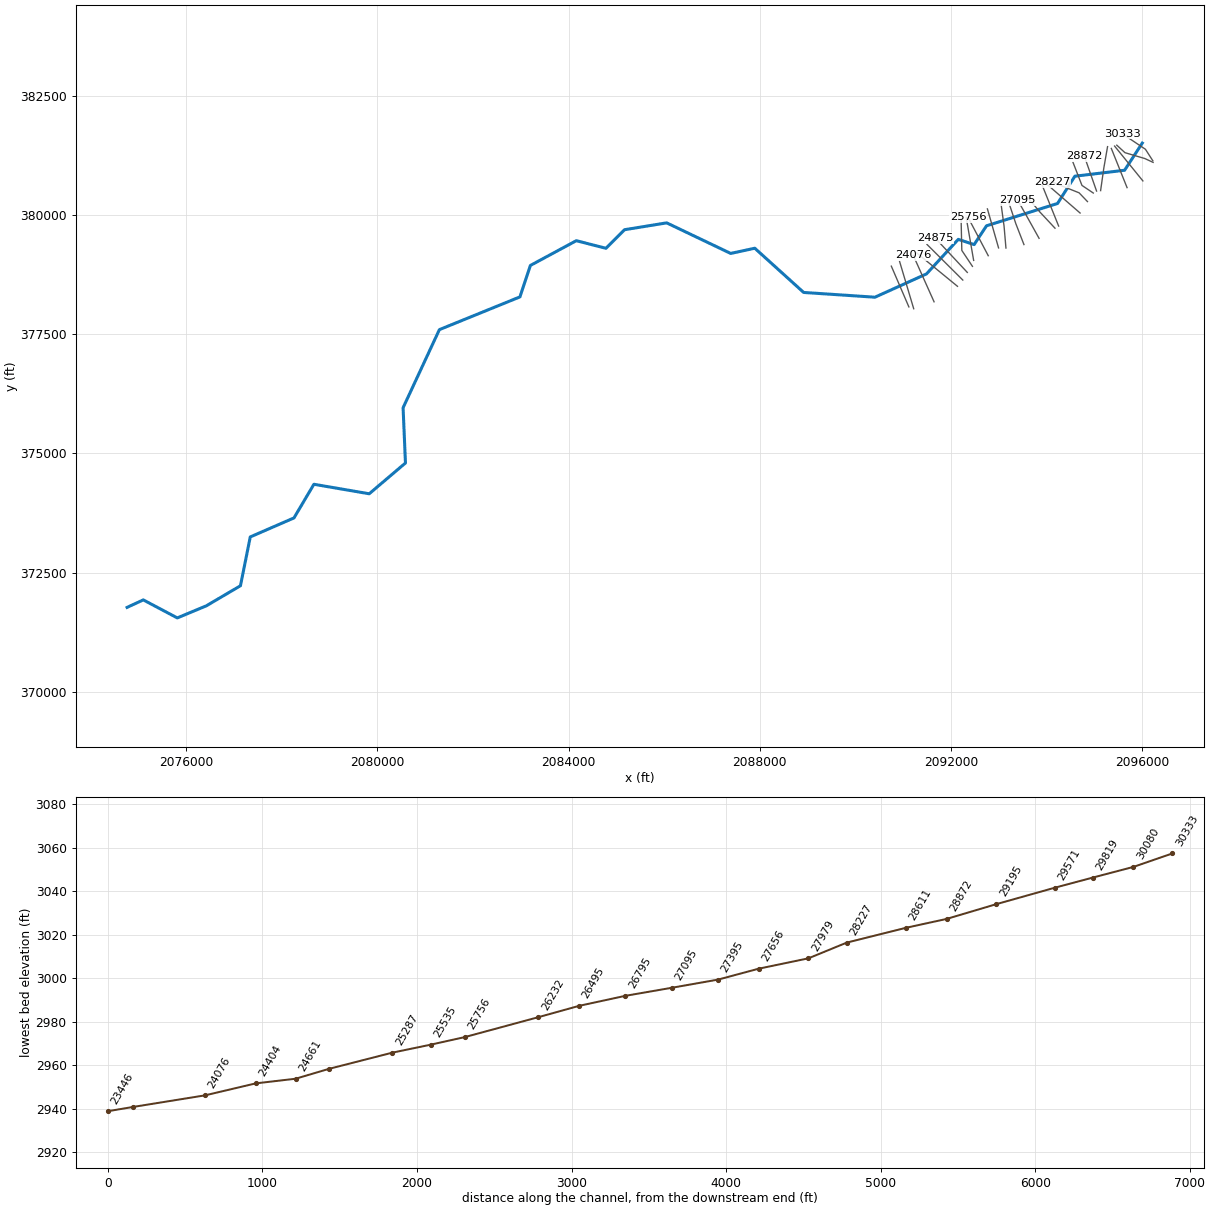
--- SFBIGCLRCK.prj (project) ---

Proj Title=SFBIGCLRCK
Current Plan=p01
Default Exp/Contr=0,0
English Units
Geom File=g01
Flow File=f01
Plan File=p01
BEGIN DESCRIPTION:
Stream Name- South Fork Big Clear Creek
Flood Zone: Zone A
Greenbrier County, WV
County-Wide Study
WVDHSEM-2018-3, Flood Risk Project
HEC-RAS Version: 5.0.7
General Notes:
For the Hydrology regression was used.
END DESCRIPTION:
DSS Export Rating Curves= 0
DSS Export Rating Curve Sorted= 0
DSS Export Volume Flow Curves= 0
DXF OffsetX= 0
DXF OffsetY= 0
DXF ScaleX= 0
DXF ScaleY= 0

--- SFBIGCLRCK.p01 (plan) ---

Plan Title=Floodplain
Program Version=5.07
Short Identifier=Floodplain
Geom File=g01
Flow File=f01
Subcritical Flow
K Sum by GR= 0
Std Step Tol= 0.01
Critical Tol= 0.01
Num of Std Step Trials= 20
Max Error Tol= 0.3
Flow Tol Ratio= 0.001
Split Flow NTrial= 30
Split Flow Tol= 0.02
Split Flow Ratio= 0.02
Log Output Level= 0
Friction Slope Method= 1
Unsteady Friction Slope Method= 2
Unsteady Bridges Friction Slope Method= 1
Parabolic Critical Depth
Global Vel Dist= 0 , 0 , 0
Global Log Level= 0
CheckData=True
Encroach Param=-1 ,0,0, 0
Mapping Interval=1HOUR
Computation Time Step Use Courant=        0
Computation Time Step Use Time Series=    0
Computation Time Step Count To Double=0
Computation Time Step Max Doubling=0
Computation Time Step Max Halving=0
Computation Time Step Residence Courant=0
Run HTab= 0
Run UNet= 0
Run Sediment= 0
Run PostProcess= 0
Run WQNet= 0
Run RASMapper=-1
UNET Theta= 0
UNET Theta Warmup= 0
UNET ZTol= 0
UNET ZSATol= 0
UNET MxIter= 0
UNET Max Iter WO Improvement= 0
UNET MaxInSteps= 0
UNET DtIC= 0
UNET DtMin= 0
UNET MaxCRTS= 0
UNET WFStab= 0
UNET SFStab= 0
UNET WFX= 1
UNET SFX= 1
UNET 1D Methodology=Finite Difference
UNET DSS MLevel= 1
UNET Pardiso=0
UNET DZMax Abort= 0
UNET Use Existing IB Tables= 0
UNET Froude Reduction=False
UNET Froude Limit= 0
UNET Froude Power= 0
UNET D1 Cores= 0
UNET D2 Coriolis=0
UNET D2 Cores= 0
UNET D2 Theta= 1
UNET D2 Theta Warmup= 1
UNET D2 Z Tol= 0.01
UNET D2 Volume Tol= 0.01
UNET D2 Max Iterations= 20
UNET D2 Equation= 0
UNET D2 RampUpFraction=0.1
UNET D2 TimeSlices= 1
UNET D2 BCVolumeCheck=0
UNET D1D2 MaxIter= 0
UNET D1D2 ZTol=0.01
UNET D1D2 QTol=0.1
UNET D1D2 MinQTol=1
Write IC File= 0
Write IC File at Fixed DateTime=0
Write IC File at Sim End=0
Echo Input=False
Echo Parameters=False
Echo Output=False
Write Detailed= 0
HDF Write Warmup=0
HDF Write Time Slices=0
HDF Flush=0
HDF Face Node Velocities=0
HDF Compression= 1
HDF Chunk Size= 1
HDF Spatial Parts= 1
HDF Use Max Rows=0
HDF Fixed Rows= 1
Calibration Method= 0
Calibration Iterations= 20
Calibration Max Change=0.05
Calibration Tolerance=0.2
Calibration Maximum=1.5
Calibration Minimum=0.5
Calibration Optimization Method= 1
WQ AD Non Conservative
WQ ULTIMATE=-1
WQ Max Comp Step=1HOUR
WQ Output Interval=15MIN
WQ Output Selected Increments= 0
WQ Output face flow=0
WQ Output face velocity=0
WQ Output face area=0
WQ Output face dispersion=0
WQ Output cell volume=0
WQ Output cell surface area=0
WQ Output cell continuity=0
WQ Output cumulative cell continuity=0
WQ Output face conc=0
WQ Output face dconc_dx=0
WQ Output face courant=0
WQ Output face peclet=0
WQ Output face adv mass=0
WQ Output face disp mass=0
WQ Output cell mass=0
WQ Output cell source sink temp=0
WQ Output nsm pathways=0
WQ Output nsm derived pathways=0
WQ Output MaxMinRange=-1
WQ Daily Max Min Mean=-1
WQ Daily Range=0
WQ Daily Time=0
WQ Create Restart=0
WQ Fixed Restart=0
WQ System Summary=0
WQ Write To DSS=0
WQ Use Fixed Temperature=0
Sorting and Armoring Iterations= 10
XS Update Threshold= 0.02
Bed Roughness Predictor= 0
Hydraulics Update Threshold= 0.02
Energy Slope Method= 1
Volume Change Method= 1
Sediment Retention Method= 0
XS Weighting Method= 0
Number of US Weighted Cross Sections= 1
Number of DS Weighted Cross Sections= 1
Upstream XS Weight=0
Main XS Weight=1
Downstream XS Weight=0
Number of DS XS's Weighted with US Boundary= 1
Upstream Boundary Weight= 1
Weight of XSs Associated with US Boundary= 0
Number of US XS's Weighted with DS Boundary= 1
Downstream Boundary Weight= 0.5
Weight of XSs Associated with DS Boundary= 0.5
Percentile Method= 0
Sediment Output Level= 3
Mass or Volume Output= 0
Output Increment Type= 1
Profile and TS Output Increment= 1
XS Output Flag= 0
XS Output Increment= 10
Write Gradation File= 0
Read Gradation Hotstart= 0
Write HDF5 File= 1
Write Binary Output= 1
Write DSS Sediment File= 0
SV Curve= 0
Specific Gage Flag= 0

--- SFBIGCLRCK.f01 (steady flow) ---

Flow Title=H3a_CombinedFlows
Program Version=5.07
Number of Profiles= 6
Profile Names=f1p,f10p,f4p,f2p,f02p,f1pplus
River Rch & RM=SFBIGCLRCK,Main            ,30333
    1620     892    1160    1380    2220    2400
River Rch & RM=SFBIGCLRCK,Main            ,29819
    1810     997    1300    1540    2470    2670
River Rch & RM=SFBIGCLRCK,Main            ,24661
    2010    1110    1450    1720    2740    2970
River Rch & RM=SFBIGCLRCK,Main            ,18926
    2660    1490    1930    2290    3620    3940
River Rch & RM=SFBIGCLRCK,Main            ,7843
    3090    1740    2250    2660    4190    4570
Boundary for River Rch & Prof#=BROWNCK,Main            , 1
Up Type= 0
Dn Type= 3
Dn Slope=0.01133
Boundary for River Rch & Prof#=BROWNCK,Main            , 2
Up Type= 0
Dn Type= 3
Dn Slope=0.01133
Boundary for River Rch & Prof#=BROWNCK,Main            , 3
Up Type= 0
Dn Type= 3
Dn Slope=0.01133
Boundary for River Rch & Prof#=BROWNCK,Main            , 4
Up Type= 0
Dn Type= 3
Dn Slope=0.01133
Boundary for River Rch & Prof#=BROWNCK,Main            , 5
Up Type= 0
Dn Type= 3
Dn Slope=0.01133
Boundary for River Rch & Prof#=BROWNCK,Main            , 6
Up Type= 0
Dn Type= 3
Dn Slope=0.01133
Boundary for River Rch & Prof#=JOBKNOBBR1,Main            , 1
Up Type= 0
Dn Type= 1
Dn Known WS=3060.49
Boundary for River Rch & Prof#=JOBKNOBBR1,Main            , 2
Up Type= 0
Dn Type= 1
Dn Known WS=3059.58
Boundary for River Rch & Prof#=JOBKNOBBR1,Main            , 3
Up Type= 0
Dn Type= 1
Dn Known WS=3059.97
Boundary for River Rch & Prof#=JOBKNOBBR1,Main            , 4
Up Type= 0
Dn Type= 1
Dn Known WS=3060.23
Boundary for River Rch & Prof#=JOBKNOBBR1,Main            , 5
Up Type= 0
Dn Type= 1
Dn Known WS=3061.06
Boundary for River Rch & Prof#=JOBKNOBBR1,Main            , 6
Up Type= 0
Dn Type= 1
Dn Known WS=3061.19
Boundary for River Rch & Prof#=OLFLDBR,Main            , 1
Up Type= 0
Dn Type= 3
Dn Slope=0.01816
Boundary for River Rch & Prof#=OLFLDBR,Main            , 2
Up Type= 0
Dn Type= 3
Dn Slope=0.01816
Boundary for River Rch & Prof#=OLFLDBR,Main            , 3
Up Type= 0
Dn Type= 3
Dn Slope=0.01816
Boundary for River Rch & Prof#=OLFLDBR,Main            , 4
Up Type= 0
Dn Type= 3
Dn Slope=0.01816
Boundary for River Rch & Prof#=OLFLDBR,Main            , 5
Up Type= 0
Dn Type= 3
Dn Slope=0.01816
Boundary for River Rch & Prof#=OLFLDBR,Main            , 6
Up Type= 0
Dn Type= 3
Dn Slope=0.01816
Boundary for River Rch & Prof#=SAMCK,Main            , 1
Up Type= 0
Dn Type= 3
Dn Slope=0.07188
Boundary for River Rch & Prof#=SAMCK,Main            , 2
Up Type= 0
Dn Type= 3
Dn Slope=0.07188
Boundary for River Rch & Prof#=SAMCK,Main            , 3
Up Type= 0
Dn Type= 3
Dn Slope=0.07188
Boundary for River Rch & Prof#=SAMCK,Main            , 4
Up Type= 0
Dn Type= 3
Dn Slope=0.07188
Boundary for River Rch & Prof#=SAMCK,Main            , 5
Up Type= 0
Dn Type= 3
Dn Slope=0.07188
Boundary for River Rch & Prof#=SAMCK,Main            , 6
Up Type= 0
Dn Type= 3
Dn Slope=0.07188
Boundary for River Rch & Prof#=SFBIGCLRCK,Main            , 1
Up Type= 0
Dn Type= 3
Dn Slope=0.01961
Boundary for River Rch & Prof#=SFBIGCLRCK,Main            , 2
Up Type= 0
Dn Type= 3
Dn Slope=0.01961
Boundary for River Rch & Prof#=SFBIGCLRCK,Main            , 3
Up Type= 0
Dn Type= 3
Dn Slope=0.01961
Boundary for River Rch & Prof#=SFBIGCLRCK,Main            , 4
Up Type= 0
Dn Type= 3
Dn Slope=0.01961
Boundary for River Rch & Prof#=SFBIGCLRCK,Main            , 5
Up Type= 0
Dn Type= 3
Dn Slope=0.01961
Boundary for River Rch & Prof#=SFBIGCLRCK,Main            , 6
Up Type= 0
Dn Type= 3
Dn Slope=0.01961
Boundary for River Rch & Prof#=SMKHSEBR,Main            , 1
Up Type= 0
Dn Type= 3
Dn Slope=0.01511
Boundary for River Rch & Prof#=SMKHSEBR,Main            , 2
Up Type= 0
Dn Type= 3
Dn Slope=0.01511
Boundary for River Rch & Prof#=SMKHSEBR,Main            , 3
Up Type= 0
Dn Type= 3
Dn Slope=0.01511
Boundary for River Rch & Prof#=SMKHSEBR,Main            , 4
Up Type= 0
Dn Type= 3
Dn Slope=0.01511
Boundary for River Rch & Prof#=SMKHSEBR,Main            , 5
Up Type= 0
Dn Type= 3
Dn Slope=0.01511
Boundary for River Rch & Prof#=SMKHSEBR,Main            , 6
Up Type= 0
Dn Type= 3
Dn Slope=0.01511
DSS Import GetInterval= 0
DSS Import GetPeak= 0
DSS Import FillOption= 0

--- SFBIGCLRCK.g01 (geometry) ---

Geom Title=Geometry
Program Version=5.07

River Reach=SFBIGCLRCK      ,Main
Reach XY= 30
     2096002.624      381505.189     2095631.954      380935.464
     2094592.229      380810.411     2094229.358      380238.822
     2092743.279      379770.594      2092483.85      379376.719
     2092152.805      379486.682     2091488.047      378762.386
     2090409.193      378273.554     2088917.708      378373.413
     2087895.147      379300.564     2087391.084      379191.287
     2086052.214      379832.433     2085170.267      379688.598
     2084781.542      379299.052     2084161.305      379458.614
     2083200.278      378939.223     2082981.618      378280.006
     2081296.388      377593.451      2080537.01      375955.672
     2080586.762      374797.543     2079828.434      374152.289
     2078671.011      374351.268     2078254.333      373645.845
     2077339.727       373247.27     2077134.432      372223.521
     2076419.242      371802.194     2075813.251      371549.376
     2075101.526      371927.283       2074762.7      371770.148

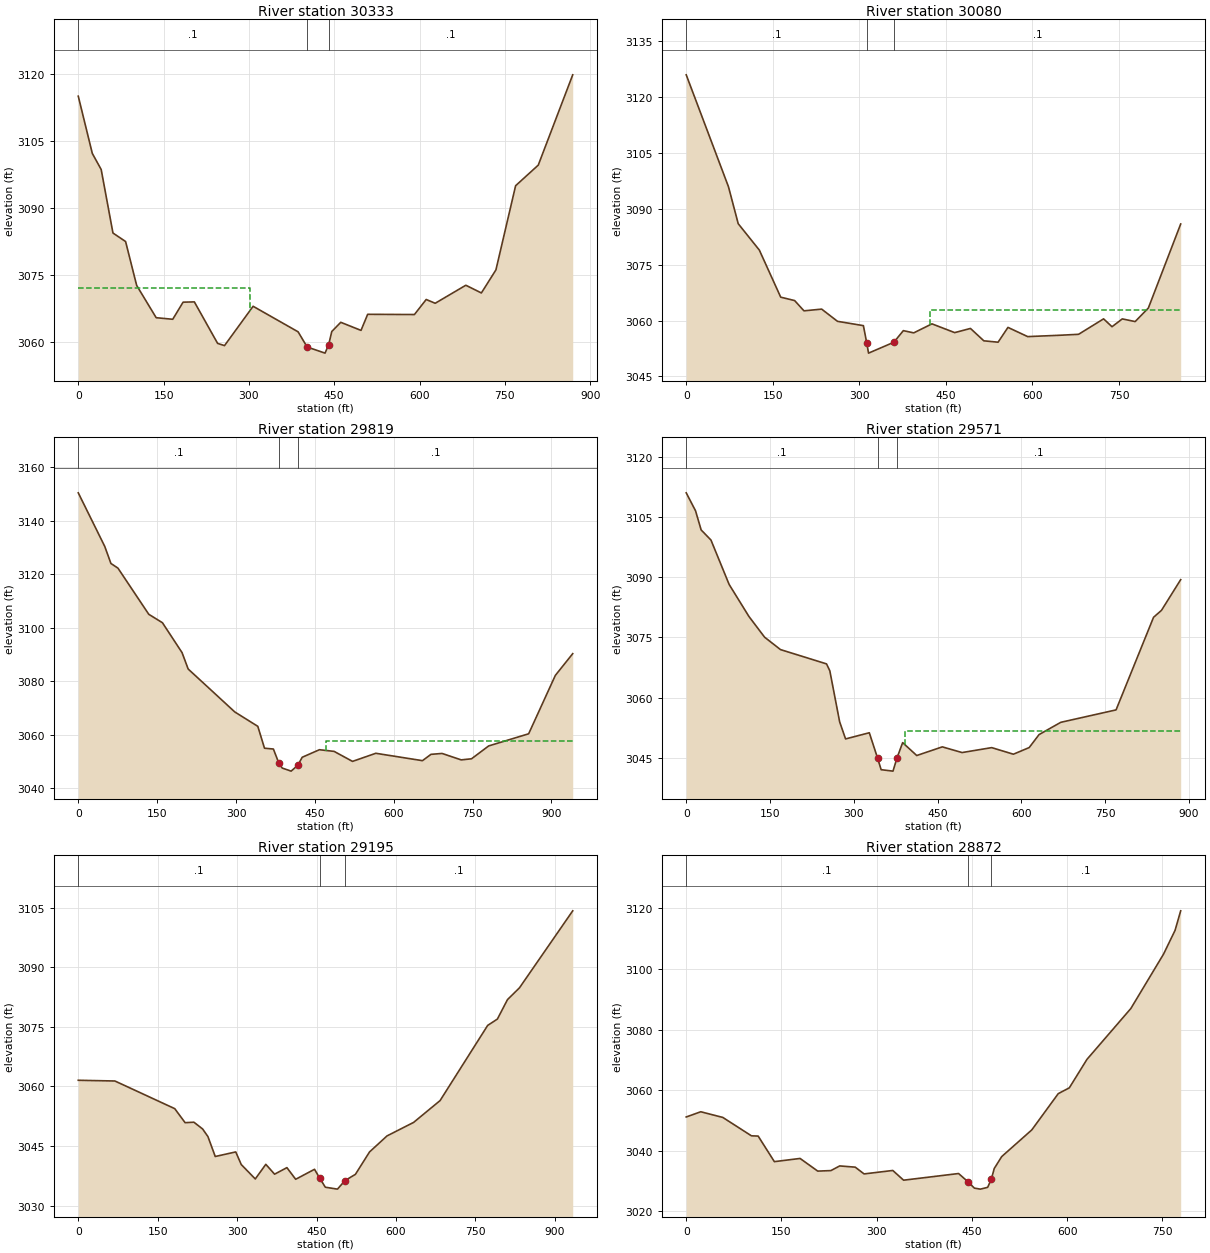
Type RM Length L Ch R = 1 ,30333   ,253,253,253
XS GIS Cut Line= 3
2096223.65583131 381133.342755662096068.00160859381375.573883325
2095585.38141506381699.776761417
#Sta/Elev= 30
       0 3115.01    24.7 3102.19    40.3 3098.59      61 3084.37    83.2 3082.47
   102.7 3072.63     137 3065.41   166.1 3065.06   184.3 3068.89   204.1 3068.95
     245 3059.66   257.1 3059.16   307.4 3067.97   386.5 3062.25   402.4 3058.85
   433.9 3057.48   440.3  3059.4   445.7 3062.32   461.5 3064.38   497.1 3062.57
   508.8 3066.17     591 3066.12   611.7 3069.49   627.5 3068.64   681.4 3072.68
   708.7 3070.95   734.3 3076.12   768.9 3094.96   808.7 3099.57   869.3 3119.79
#Mann= 3 ,-1 , 0
       0      .1       0   402.4    .045       0   440.3      .1       0
#XS Ineff= 2 , 0
          301.82 3072.02
Permanent Ineff=
       F       F
Bank Sta=402.4,440.3
XS Rating Curve= 0 ,0
Exp/Cntr=0.3,0.1

Type RM Length L Ch R = 1 ,30080   ,261.4,261.4,261.4
XS GIS Cut Line= 4
2096228.63306641381100.2002960932096054.51307328381181.456292885
2095639.79090784381303.8679244162095468.83673277381461.103554571
#Sta/Elev= 30
       0 3125.89    73.2 3095.88    90.1 3085.96   126.7 3078.89   163.7 3066.27
   187.9 3065.35     204  3062.6   234.7 3063.06   262.1 3059.79     307 3058.63
  312.71 3054.06   315.9 3051.26   359.8 3054.18   376.2 3057.29   394.2 3056.69
   425.8 3059.11   465.2 3056.76   492.5 3057.88   515.7 3054.56   540.4 3054.19
   557.5 3058.16   591.7 3055.69   648.7 3056.06   679.9 3056.31   723.2 3060.45
   737.8 3058.34   755.6 3060.44   777.9 3059.72   800.8 3063.36   856.8 3085.89
#Mann= 3 ,-1 , 0
       0      .1       0  312.71    .045       0   359.8      .1       0
#XS Ineff= 2 , 0
                          422.84         3062.72
Permanent Ineff=
       F       F
Bank Sta=312.71,359.8
XS Rating Curve= 0 ,0
Exp/Cntr=0.3,0.1

Type RM Length L Ch R = 1 ,29819   ,248.1,248.1,248.1
XS GIS Cut Line= 2
2096014.88997502380711.6266323672095422.93409468381442.300712045
#Sta/Elev= 30
       0 3150.41    50.4 3130.37    62.1 3124.01    75.5 3122.26   134.1 3105.01
   160.1 3101.85   197.4 3090.68     209 3084.56   297.7  3068.5   341.5 3063.12
   354.2 3054.95   371.1 3054.64   381.2 3049.52   387.9 3047.53   404.8 3046.38
   417.5 3048.55   425.9 3051.56   458.6 3054.38   486.6 3053.76   521.6 3050.02
   565.9 3053.05   654.6 3050.29   670.8 3052.65   691.9 3052.99   728.3 3050.58
   747.9 3050.99   780.5 3055.79   856.6 3060.34   907.3 3082.15   940.4 3090.29
#Mann= 3 ,-1 , 0
       0      .1       0   381.2    .045       0   417.5      .1       0
#XS Ineff= 2 , 0
                          471.85         3057.56
Permanent Ineff=
       F       F
Bank Sta=381.2,417.5
XS Rating Curve= 0 ,0
Exp/Cntr=0.3,0.1

Type RM Length L Ch R = 1 ,29571   ,376.2,376.2,376.2
XS GIS Cut Line= 2
2095683.86833028380571.0361604732095354.51667964381392.816728291
#Sta/Elev= 30
       0 3111.07    16.7 3106.58    26.7 3101.82    44.3 3099.29    76.8 3088.23
   112.2 3080.25   140.2 3075.09   168.7 3071.98   251.2 3068.41   257.1 3066.69
   274.7 3053.95   285.3  3049.7   327.8 3051.24   342.6 3044.91     349 3042.03
   370.2 3041.67   377.2 3044.88   387.5 3048.78   412.7 3045.56   458.5 3047.72
   493.9  3046.3   546.9 3047.53   585.8 3045.89   614.1 3047.55   631.7 3050.78
   670.6 3053.84   769.6 3056.94   836.7 3080.03   850.9 3081.76   885.3 3089.42
#Mann= 3 ,-1 , 0
       0      .1       0   342.6    .045       0   377.2      .1       0
#XS Ineff= 2 , 0
                          391.83         3051.79
Permanent Ineff=
       F       F
Bank Sta=342.6,377.2
XS Rating Curve= 0 ,0
Exp/Cntr=0.3,0.1

Type RM Length L Ch R = 1 ,29195   ,322.3,322.3,322.3
XS GIS Cut Line= 3
     2095130.228       380508.17     2095197.594      380982.252
     2095275.763      381430.408
#Sta/Elev= 30
       0 3061.54    69.2 3061.36   182.2  3054.4   201.8 3050.87   218.4 3050.99
   234.9 3049.28   244.9 3047.37   258.7 3042.36   297.4 3043.51   307.8 3040.34
   334.3 3036.71   354.2 3040.39   370.8 3037.91     394 3039.56   410.6 3036.63
   446.2 3039.14     456 3036.91   466.6 3034.63   489.5 3034.15   503.7  3036.3
   523.4 3037.87   550.1 3043.51   583.1 3047.54   633.3 3050.94   683.3 3056.43
   773.2 3075.35   791.5 3076.94   810.6 3081.84   833.2  3084.8   933.8 3104.18
#Mann= 3 ,-1 , 0
       0      .1       0     456    .045       0   503.7      .1       0
Bank Sta=456,503.7
XS Rating Curve= 0 ,0
Exp/Cntr=0.3,0.1

Type RM Length L Ch R = 1 ,28872   ,261.4,261.4,261.4
XS GIS Cut Line= 2
     2095045.642      380499.3322094788.70419983381234.430217832
#Sta/Elev= 30
       0 3051.16    22.9 3052.88    57.6 3051.01   102.7 3044.94   113.3 3044.85
   138.8 3036.41   179.3 3037.47   207.1 3033.29   227.9 3033.46   241.7    3035
   266.2 3034.59   280.1 3032.36   325.3  3033.5   342.3 3030.29   428.9 3032.49
   443.6 3029.79   453.8 3027.67   463.3 3027.34   474.7 3027.93   480.4 3030.57
   485.1 3034.16   496.8 3038.08   544.2 3046.89   585.9 3058.87   603.3 3060.78
   631.1 3070.18   700.2 3086.97   751.7 3104.93   769.8 3112.75   778.7 3119.22
#Mann= 3 ,-1 , 0
       0      .1       0   443.6    .045       0   480.4      .1       0
Bank Sta=443.6,480.4
XS Rating Curve= 0 ,0
Exp/Cntr=0.3,0.1

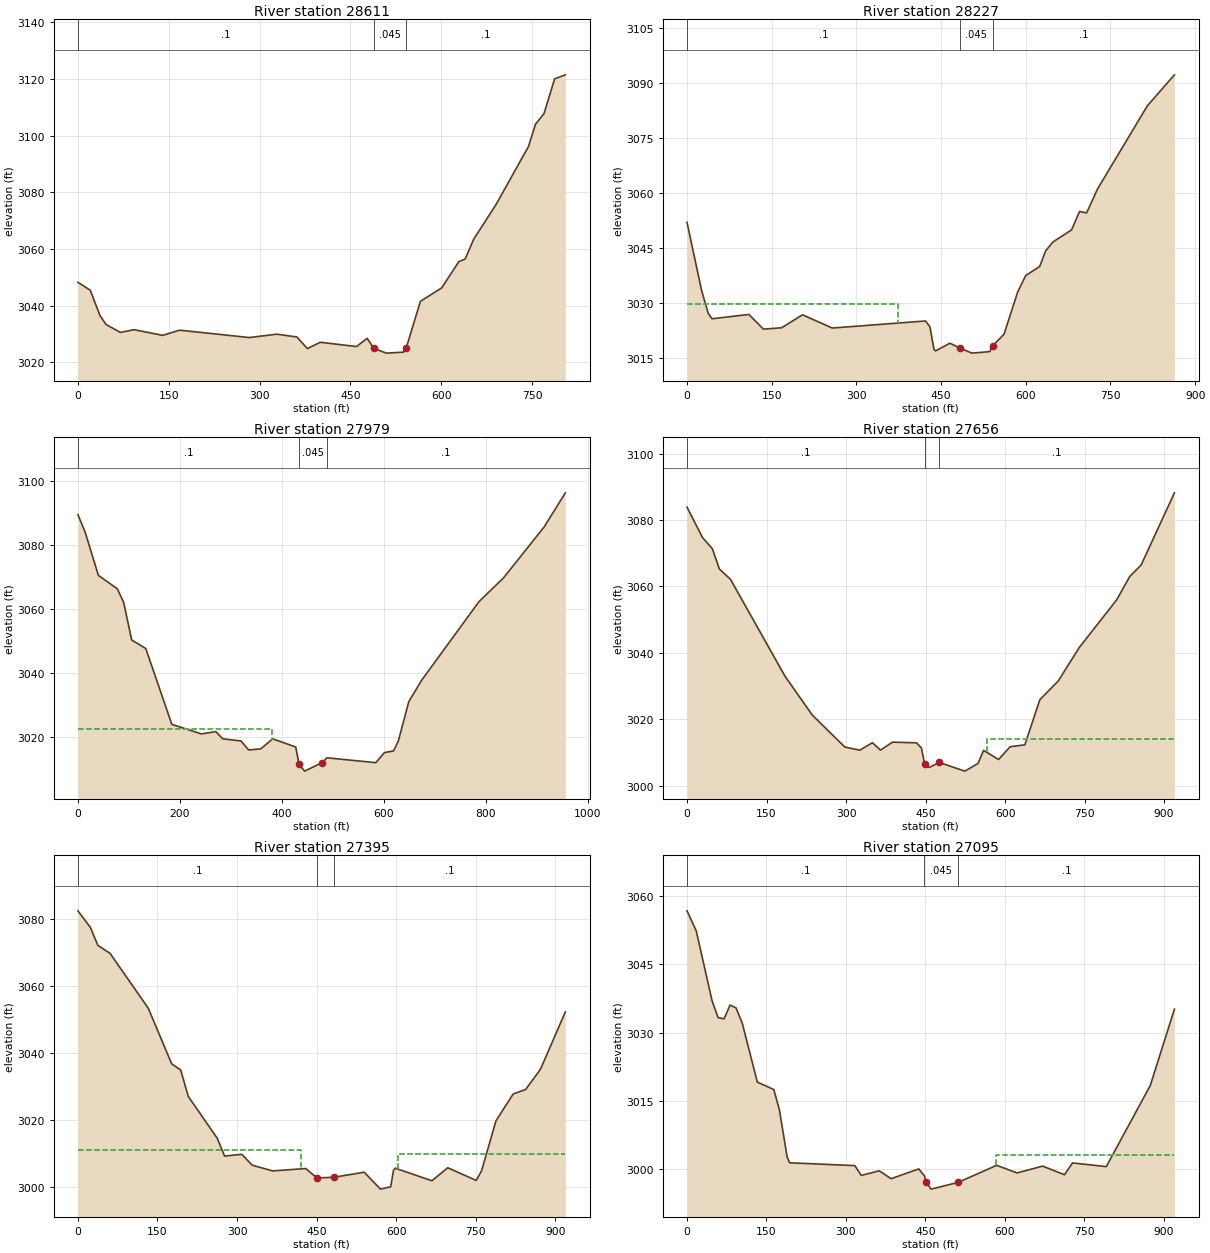
Type RM Length L Ch R = 1 ,28611   ,384.4,384.4,384.4
XS GIS Cut Line= 3
2094977.14828664380457.8980615572094740.29819498380617.361489604
2094552.69416198381101.614399778
#Sta/Elev= 30
       0 3048.27    20.4 3045.46    36.5 3036.51    46.4  3033.4    70.1 3030.58
    92.7 3031.55   140.1 3029.55   167.8 3031.38   283.2 3028.77   328.3 3029.96
   361.6 3028.98     379 3024.88   400.3 3027.11   460.1  3025.6   477.7 3028.49
   488.7 3024.95   509.3 3023.28   537.5 3023.62     542    3025   565.6 3041.56
   600.8 3046.29     629 3055.54   639.5 3056.49   653.6 3063.45   690.9 3075.84
   744.2 3096.22   755.6 3103.99   769.7 3107.77   787.2 3120.01   804.9 3121.43
#Mann= 3 ,-1 , 0
       0      .1       0   488.7    .045       0     542      .1       0
Bank Sta=488.7,542
XS Rating Curve= 0 ,0
Exp/Cntr=0.3,0.1

Type RM Length L Ch R = 1 ,28227   ,247.9,247.9,247.9
XS GIS Cut Line= 3
2094855.38043607380278.6107277562094680.22543613380462.451099597
2094114.22870077380688.270768945
#Sta/Elev= 30
       0 3052.11    25.9 3033.51    37.6 3027.27    44.3 3025.82   109.5    3027
   135.3 3022.99   167.5 3023.36   204.6  3026.9   257.2 3023.29   422.5 3025.22
   430.3  3023.6   437.4 3017.47   440.2 3017.05   465.6 3019.15   483.7 3017.82
   504.5 3016.45   536.3 3016.86   541.2 3018.43   561.4 3021.59   585.7 3033.12
   599.9 3037.61   624.6 3040.06   635.2 3044.34   648.3 3046.78   681.1 3050.05
   695.2 3055.07   707.8 3054.69     727 3061.19   815.3 3083.88   863.3 3092.34
#Mann= 3 ,-1 , 0
       0      .1       0   483.7    .045       0   541.2      .1       0
#XS Ineff= 2 , 0
          374.42 3029.85
Permanent Ineff=
       F       F
Bank Sta=483.7,541.2
XS Rating Curve= 0 ,0
Exp/Cntr=0.3,0.1

Type RM Length L Ch R = 1 ,27979   ,322.3,322.3,322.3
XS GIS Cut Line= 2
     2094700.964      380038.751      2093979.62      380666.012
#Sta/Elev= 30
       0  3089.5    14.1 3084.05    40.1  3070.5    77.3 3066.28    89.9 3061.94
   105.4 3050.27   133.1 3047.59   184.2 3023.86   242.4 3020.86   270.3 3021.59
   284.2 3019.32   319.8 3018.67   334.8 3015.85   358.7 3016.19   381.9 3019.33
   427.2 3016.77   433.7 3011.32   444.6 3009.22   479.4 3011.91   488.2 3013.39
   584.2 3011.87   601.1 3015.02   619.1 3015.55   628.4 3018.68   648.9 3030.96
   674.8 3037.83   786.6 3062.27   834.8 3069.72   914.5 3085.68   955.9 3096.32
#Mann= 3 ,-1 , 0
       0      .1       0   433.7    .045       0   488.2      .1       0
#XS Ineff= 2 , 0
          379.98 3022.43
Permanent Ineff=
       F       F
Bank Sta=433.7,479.4
XS Rating Curve= 0 ,0
Exp/Cntr=0.3,0.1

Type RM Length L Ch R = 1 ,27656   ,261.7,261.7,261.7
XS GIS Cut Line= 2
     2094252.102      379765.573     2093909.214      380618.773
#Sta/Elev= 30
       0 3083.87    29.1 3074.77    47.9 3071.34    60.9  3065.3    82.2  3062.1
   184.7 3033.04   236.3 3021.32   297.8 3011.68   326.1 3010.75   349.8    3013
     365 3010.76   387.6 3013.16     433 3012.96   442.2  3011.4   448.1  3006.7
     457 3005.56   475.9 3007.04   524.1 3004.44   548.9 3006.74   559.5 3010.69
   587.8 3007.94   609.6 3011.79   637.3 3012.35   665.6 3025.92   700.4 3031.58
   739.8 3041.59   810.5 3055.97   835.3 3063.03   856.7 3066.46   919.5 3088.18
#Mann= 3 ,-1 , 0
       0      .1       0   448.1    .045       0   475.9      .1       0
#XS Ineff= 2 , 0
                          565.31         3014.19
Permanent Ineff=
       F       F
Bank Sta=448.1,475.9
XS Rating Curve= 0 ,0
Exp/Cntr=0.3,0.1

Type RM Length L Ch R = 1 ,27395   ,300,300,300
XS GIS Cut Line= 3
     2094176.036      379720.755     2093859.465      380060.648
     2093567.261      380409.045
#Sta/Elev= 30
       0 3082.55    23.6 3077.58    37.5 3072.26    60.7 3069.84   132.7 3053.46
   176.8 3036.87   193.8 3035.02   208.2 3027.11   262.7 3014.65   276.6 3009.31
   309.1 3009.84   328.6  3006.6   367.1 3004.88   429.9 3005.59   450.7 3002.77
   482.9 3002.98   539.9 3004.49   570.5 2999.44   589.9 3000.15     595 3005.01
   598.5  3005.7   667.5 3001.94   697.5 3005.82   751.1 3002.04   761.2 3004.89
   788.3 3019.81   820.9 3027.87   844.2 3029.17   872.2  3035.2   919.2 3052.36
#Mann= 3 ,-1 , 0
       0      .1       0   450.7    .045       0   482.9      .1       0
#XS Ineff= 2 , 0
          420.24 3011.09  604.43         3010.05
Permanent Ineff=
       F       F
Bank Sta=450.7,482.9
XS Rating Curve= 0 ,0
Exp/Cntr=0.3,0.1

Type RM Length L Ch R = 1 ,27095   ,300,300,300
XS GIS Cut Line= 3
     2093842.636      379508.335     2093619.047       379910.89
     2093393.843      380311.356
#Sta/Elev= 30
       0 3056.74    17.4 3052.36    47.4 3036.95    58.7 3033.31      70 3033.03
    81.2 3036.05    92.4 3035.46   104.4 3032.03   132.7 3019.15   163.8 3017.53
   174.4 3013.05   188.9 3002.77   193.5 3001.45   316.7 3000.83   328.9 2998.68
   362.7 2999.69   385.2 2997.96   437.4 3000.11     448 2998.57   451.9 2997.15
   460.5 2995.67   512.1 2997.16   584.4  3000.9   622.9 2999.22   671.1 3000.72
   712.5 2998.83   727.5 3001.42   791.3 3000.61   874.3 3018.41   919.9 3035.17
#Mann= 3 ,-1 , 0
       0      .1       0     448    .045       0   512.1      .1       0
#XS Ineff= 2 , 0
                          583.96         3003.19
Permanent Ineff=
       F       F
Bank Sta=451.9,512.1
XS Rating Curve= 0 ,0
Exp/Cntr=0.3,0.1

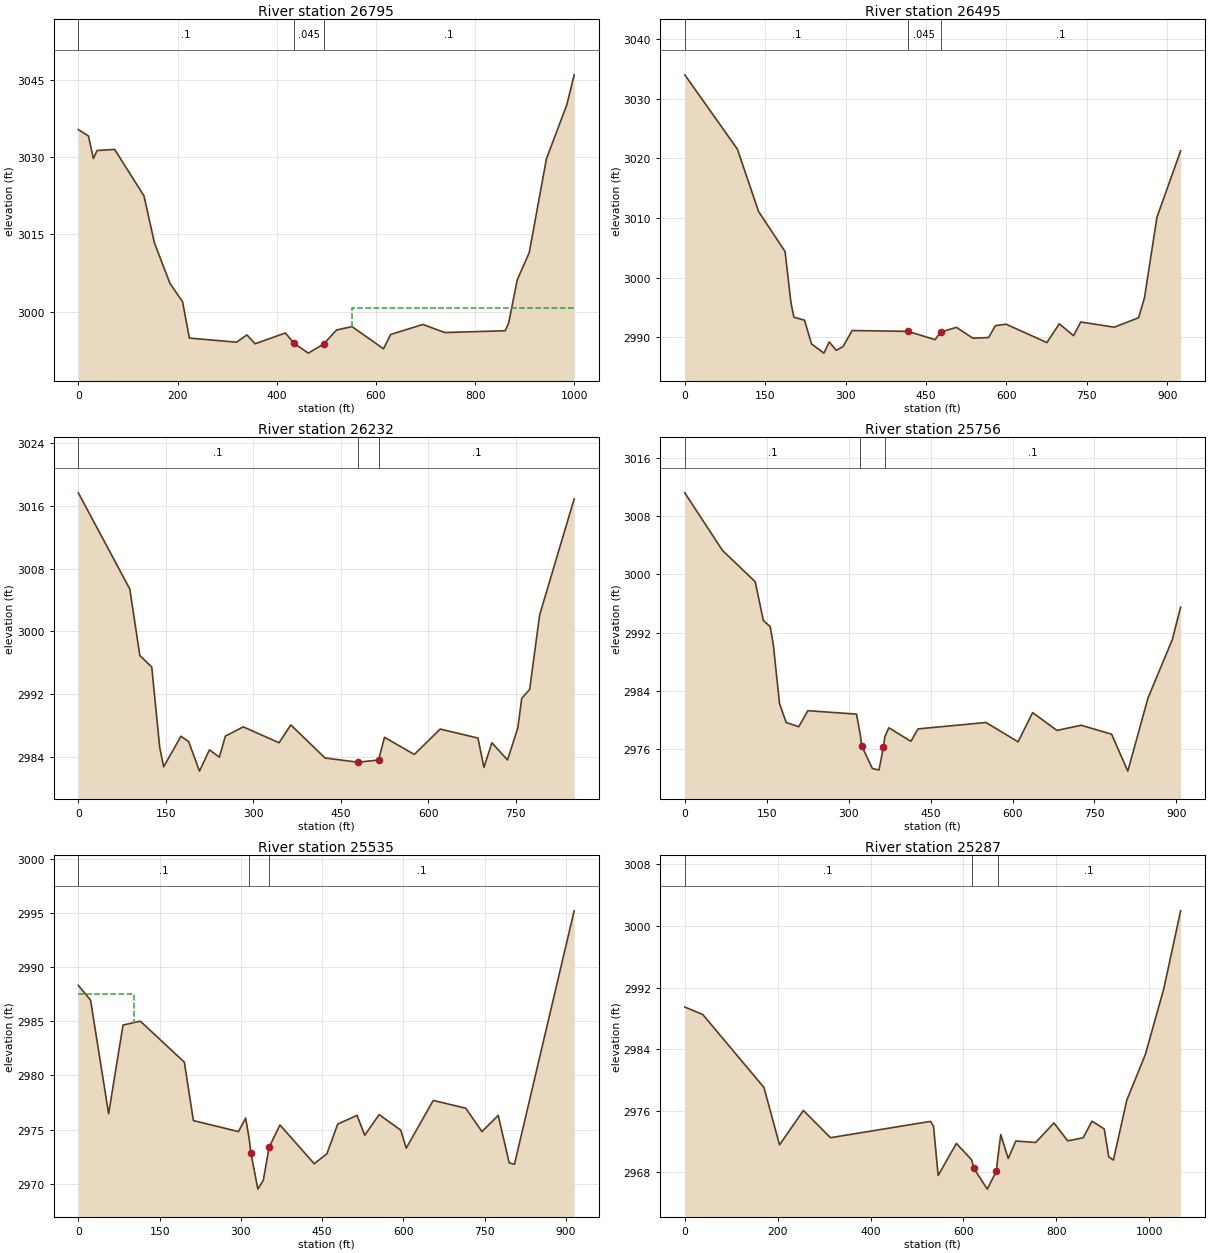
Type RM Length L Ch R = 1 ,26795   ,300,300,300
XS GIS Cut Line= 3
      2093526.43      379377.159     2093356.884      379814.592
2093189.87613224380318.128727252
#Sta/Elev= 30
       0 3035.33    20.5 3034.08    30.3 3029.71    37.7 3031.26    73.2 3031.48
   132.4 3022.46   153.5 3013.32   184.8 3005.49   210.2 3001.93   223.9 2994.89
   318.9 2994.09     340  2995.5   356.4 2993.78   417.4 2995.88     435 2993.86
   463.7 2991.97   494.4 2993.73   520.7 2996.46   551.9 2997.11   615.3 2992.81
   629.7 2995.59   694.8 2997.53   738.8 2995.96   860.8 2996.31   867.7 2997.83
     885  3006.2   909.1 3011.45   943.8 3029.64   985.2 3040.22   999.7 3045.94
#Mann= 3 ,-1 , 0
       0      .1       0     435    .045       0   494.4      .1       0
#XS Ineff= 2 , 0
                          552.03         3000.72
Permanent Ineff=
       F       F
Bank Sta=435,494.4
XS Rating Curve= 0 ,0
Exp/Cntr=0.3,0.1

Type RM Length L Ch R = 1 ,26495   ,262.3,262.3,262.3
XS GIS Cut Line= 3
     2093149.848      379304.333     2093110.636      379761.989
     2093048.125      380223.492
#Sta/Elev= 30
       0 3034.01    98.2 3021.54   137.7 3011.08   187.1 3004.38     198 2995.85
   203.6 2993.37   223.3 2992.88   236.5 2988.88   259.6 2987.35   269.4 2989.23
   282.6 2987.83   295.1 2988.43   312.2 2991.14   416.4    2991     467 2989.61
   477.7  2990.9   506.8 2991.67   537.6 2989.85   566.8 2989.97   579.6 2991.96
   599.5  2992.2   675.6 2989.12   698.8 2992.27   725.3 2990.27   738.8 2992.57
   801.4  2991.7   846.7 2993.29   857.7 2996.65   880.9 3010.12   925.1 3021.26
#Mann= 3 ,-1 , 0
       0      .1       0   416.4    .045       0   477.7      .1       0
Bank Sta=416.4,477.7
XS Rating Curve= 0 ,0
Exp/Cntr=0.3,0.1

Type RM Length L Ch R = 1 ,26232   ,476.8,476.8,476.8
XS GIS Cut Line= 2
2092995.26328791379307.2966371612092762.20580865380125.169157558
#Sta/Elev= 30
       0 3017.68    88.3  3005.4   105.5 2996.91   125.9 2995.45   139.6 2985.17
   146.4 2982.71     176 2986.61   189.2 2985.93   207.8 2982.16   224.9 2984.88
   241.9 2983.94   252.2 2986.63   282.9 2987.81   344.3 2985.78   364.4 2988.06
   423.3 2983.83   479.8  2983.3   514.9 2983.58   525.1 2986.48   576.3 2984.29
   620.6 2987.53   685.4 2986.38   695.7 2982.63   709.3 2985.78   736.1 2983.58
   753.7 2987.66   760.5 2991.45   774.1 2992.59   791.2 3002.09   850.4  3016.9
#Mann= 3 ,-1 , 0
       0      .1       0   479.8    .045       0   514.9      .1       0
Bank Sta=479.8,514.9
XS Rating Curve= 0 ,0
Exp/Cntr=0.3,0.1

Type RM Length L Ch R = 1 ,25756   ,220.9,220.9,220.9
XS GIS Cut Line= 2
2092779.57655244379143.7221330822092356.88845341379947.119033648
#Sta/Elev= 30
       0  3011.2      69 3003.29   128.9 2998.99   143.8 2993.68   156.4 2992.81
   162.3 2990.23   173.4 2982.27   185.6 2979.66   208.7 2979.08   225.3 2981.28
   314.4 2980.81   321.4 2977.93     324 2976.44   343.5 2973.33   355.6 2973.14
   363.7  2976.3   366.2  2977.7   373.6 2978.94   413.9 2977.07   427.1 2978.78
   551.5 2979.66   610.3    2977   636.8 2981.02   681.3 2978.57   725.8 2979.28
   781.4 2978.05   811.1 2972.98   848.1 2983.03   892.5 2991.02   907.8  2995.5
#Mann= 3 ,-1 , 0
       0      .1       0   321.4    .045       0   366.2      .1       0
Bank Sta=324,363.7
XS Rating Curve= 0 ,0
Exp/Cntr=0.3,0.1

Type RM Length L Ch R = 1 ,25535   ,247.2,247.2,247.2
XS GIS Cut Line= 2
2092474.14097403379045.2879182382092317.80427987379947.119033648
#Sta/Elev= 30
       0 2988.33    22.6 2986.96    55.9 2976.46    82.5 2984.66   114.4 2985.02
   195.7 2981.23   212.4 2975.83   295.6 2974.81   308.9 2976.06   315.2 2974.21
   318.7 2972.82   331.4 2969.49   341.4  2970.3   352.2 2973.36   372.2 2975.42
   435.5 2971.84   458.8 2972.75   478.8  2975.5   514.5 2976.31   528.7 2974.47
   555.3 2976.38   595.3 2974.94   605.3 2973.28   655.2 2977.69   715.2 2976.97
   745.1 2974.81   775.1 2976.31   795.4 2971.92   805.1 2971.79   915.3 2995.22
#Mann= 3 ,-1 , 0
       0      .1       0   315.2    .045       0   352.2      .1       0
#XS Ineff= 2 , 0
          102.87 2987.55
Permanent Ineff=
       F       F
Bank Sta=318.7,352.2
XS Rating Curve= 0 ,0
Exp/Cntr=0.3,0.1

Type RM Length L Ch R = 1 ,25287   ,412.1,412.1,412.1
XS GIS Cut Line= 3
2092448.67721588378920.5844909552092226.49531546379254.776712219
2092211.27705067 379920.84982121
#Sta/Elev= 30
       0 2989.48    38.6 2988.52   170.4 2979.04     204 2971.58   255.3 2976.05
   313.7 2972.51   529.1 2974.63   535.6    2974   545.5  2967.6   584.8 2971.77
   617.7 2969.63   622.6 2968.51   651.4 2965.83   670.7 2968.16   673.5 2969.65
   680.3 2972.91   696.4 2969.81   712.8 2972.08   755.5 2971.89   794.9 2974.43
   824.4  2972.1   857.7  2972.5   876.9 2974.66   903.2 2973.64     913 2970.01
   922.9 2969.61   951.7 2977.38   991.8 2983.34  1031.2 2991.82  1067.6 3001.98
#Mann= 3 ,-1 , 0
       0      .1       0   617.7    .045       0   673.5      .1       0
Bank Sta=622.6,670.7
XS Rating Curve= 0 ,0
Exp/Cntr=0.3,0.1

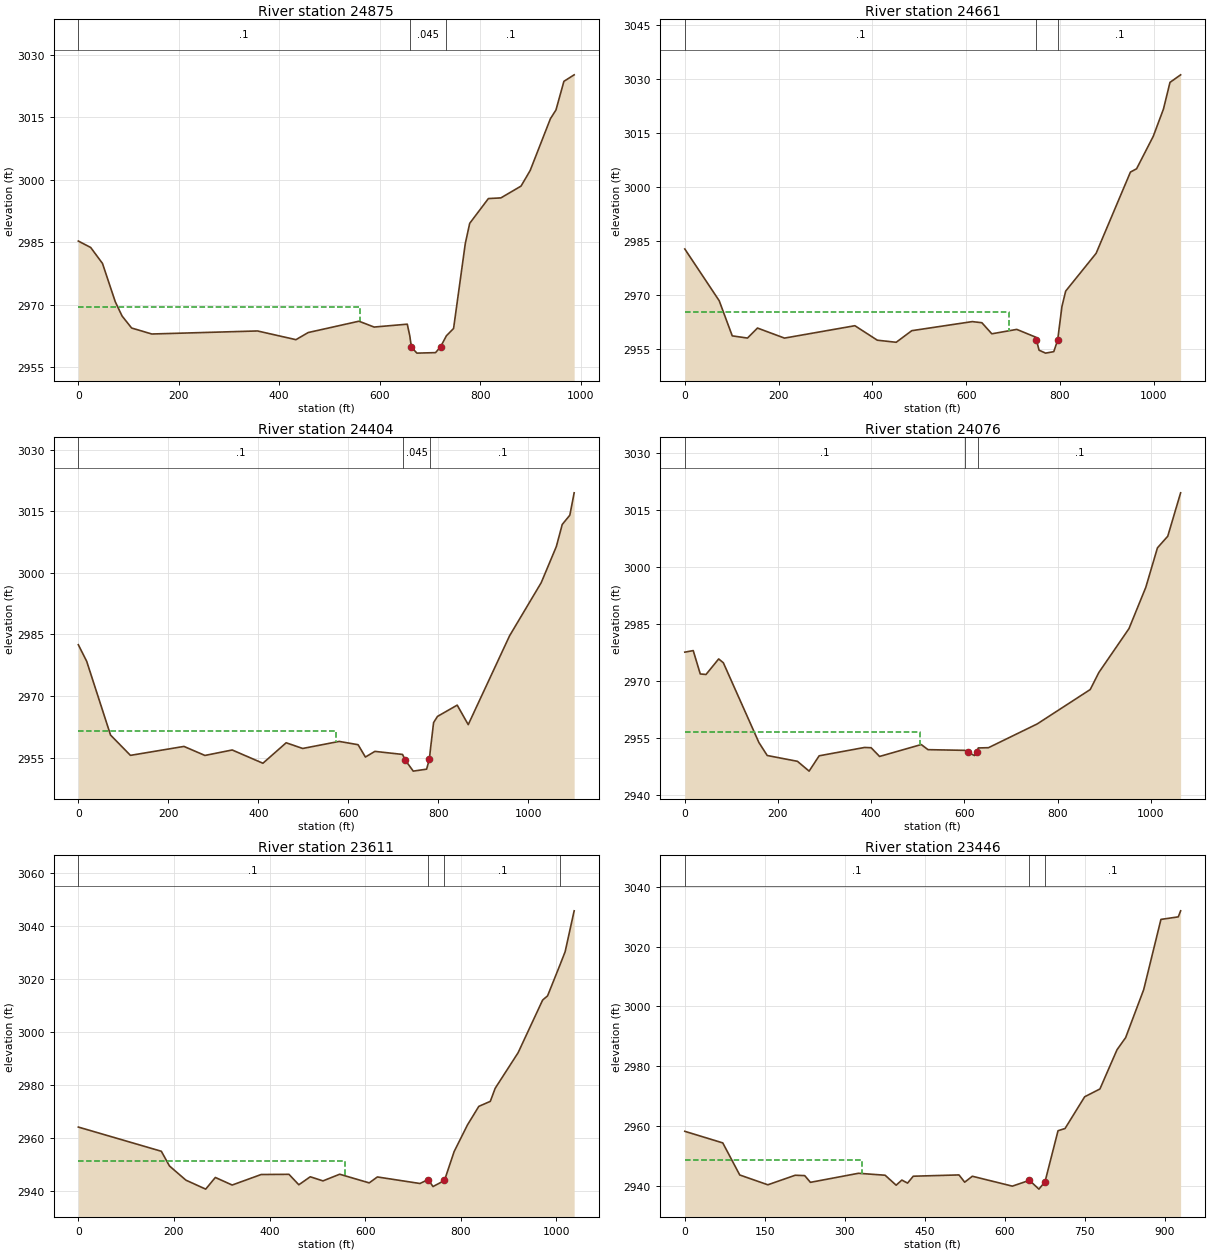
Type RM Length L Ch R = 1 ,24875   ,214,214,214
XS GIS Cut Line= 2
2092341.55762914 378793.199036452091668.44130704379515.532465969
#Sta/Elev= 30
       0 2985.24    24.6  2983.7    48.1 2979.87    73.6 2970.66    87.1 2967.25
   106.1 2964.37   146.3 2962.93   356.8 2963.66   433.3 2961.57   457.7 2963.28
   558.8    2966     589  2964.6     655 2965.29   659.9 2962.55   663.3 2959.76
   674.2 2958.34   711.3 2958.46   721.3 2959.86   732.9  2962.5   747.2 2964.26
   770.5 2984.63   779.3 2989.49   816.5 2995.44   841.4  2995.6   881.5 2998.43
   899.7 3002.17     940  3014.6   951.1 3016.71   966.9 3023.58   987.3 3025.14
#Mann= 3 ,-1 , 0
       0      .1       0   659.9    .045       0   732.9      .1       0
#XS Ineff= 2 , 0
          560.15 2969.33
Permanent Ineff=
       F       F
Bank Sta=663.3,721.3
XS Rating Curve= 0 ,0
Exp/Cntr=0.3,0.1

Type RM Length L Ch R = 1 ,24661   ,257.4,257.4,257.4
XS GIS Cut Line= 2
 2092247.0034364378633.2861294862091498.40142324379379.902460911
#Sta/Elev= 30
       0 2982.74    73.4 2968.37   101.2 2958.62   133.7 2958.01     155 2960.79
   212.6    2958   362.7 2961.44   410.5 2957.42   450.8 2956.84     484 2960.06
     613 2962.58   633.5 2962.27   654.7 2959.19   707.9 2960.42   748.5 2958.25
   749.7 2957.51   755.5 2954.64   769.4 2953.83   786.8 2954.24   794.9 2957.36
   796.1 2958.51   804.2 2966.76   812.2 2971.05   877.1 2981.53   950.3 3004.09
   963.4    3005     999 3014.03  1020.7 3021.58  1034.6 3028.98  1057.3 3031.08
#Mann= 3 ,-1 , 0
       0      .1       0   748.5    .045       0   796.1      .1       0
#XS Ineff= 2 , 0
          690.77 2965.22
Permanent Ineff=
       F       F
Bank Sta=749.7,794.9
XS Rating Curve= 0 ,0
Exp/Cntr=0.3,0.1

Type RM Length L Ch R = 1 ,24404   ,328.1,328.1,328.1
XS GIS Cut Line= 2
2092135.80525938 378502.231135142091283.94779613379201.191104985
#Sta/Elev= 30
       0  2982.5    18.6 2978.45    71.6 2960.49   115.8 2955.54   234.7 2957.72
   281.4 2955.52     342 2956.85   410.2 2953.62   461.9 2958.61   498.6 2957.22
   579.7 2958.94   621.7 2958.14     638 2955.13     659 2956.51   720.5 2955.77
   726.6 2954.38   744.3  2951.7     774 2952.18  780.09 2954.58   782.3 2956.82
   789.5 2963.52   798.1 2965.03     842 2967.78   866.5 2963.03   958.4 2984.68
  1028.7 2997.62  1062.3 3006.42  1075.4  3011.8  1092.3 3014.06  1101.9 3019.51
#Mann= 3 ,-1 , 0
       0      .1       0   720.5    .045       0   782.3      .1       0
#XS Ineff= 2 , 0
          572.99  2961.4
Permanent Ineff=
       F       F
Bank Sta=726.6,780.09
XS Rating Curve= 0 ,0
Exp/Cntr=0.3,0.1

Type RM Length L Ch R = 1 ,24076   ,464.5,464.5,464.5
XS GIS Cut Line= 2
2091645.91374778 378177.659541872091211.64515288379148.973632465
#Sta/Elev= 30
       0 2977.56    18.1 2977.97    33.2 2971.81    45.5 2971.67    72.7 2975.77
    82.7 2974.77     159 2953.74   176.9 2950.31   241.7 2948.78   266.8 2946.19
   288.3 2950.23   385.7 2952.43   399.8 2952.36     418 2950.06   507.4  2953.2
   521.9 2951.85     601 2951.67   608.2 2951.12   621.6  2950.3   626.2 2951.23
   629.8  2952.3   651.7 2952.37   756.2 2958.63     870  2967.7   888.5 2972.19
   953.2 2983.77   989.2 2994.63  1014.3 3005.07  1036.4 3008.13    1064 3019.57
#Mann= 3 ,-1 , 0
       0      .1       0     601    .045       0   629.8      .1       0
#XS Ineff= 2 , 0
          505.68 2956.53
Permanent Ineff=
       F       F
Bank Sta=608.2,626.2
XS Rating Curve= 0 ,0
Exp/Cntr=0.3,0.1

Type RM Length L Ch R = 1 ,23611   ,165.3,165.3,165.3
XS GIS Cut Line= 2
2091220.05272791378031.7050508332090924.10672249379025.697612496
#Sta/Elev= 30
       0 2964.23   173.6 2955.12   190.7 2949.57     225 2944.25   266.4 2940.87
   286.6 2945.26   321.8 2942.41   382.4 2946.37   440.6 2946.44   461.2 2942.51
   485.1 2945.52   511.7 2943.97   546.7 2946.48   608.4 2943.22   625.5 2945.45
   714.5 2942.99   731.6 2944.45   741.9 2941.84   765.8 2944.12     786 2954.98
   813.8 2964.99   837.7 2972.02   861.7  2973.9   871.9 2978.82   919.9 2992.22
   971.2 3012.04   981.5 3013.61 1007.81 3025.42  1018.2  3030.2  1037.1 3045.61
#Mann= 4 ,-1 , 0
       0      .1       0   731.6    .045       0   765.8      .1       0
 1007.81      .1       0
#XS Ineff= 2 , 0
          558.82 2951.35
Permanent Ineff=
       F       F
Bank Sta=731.6,765.8
XS Rating Curve= 0 ,0
Exp/Cntr=0.3,0.1

Type RM Length L Ch R = 1 ,23446   ,335,335,335
XS GIS Cut Line= 2
 2091118.7233891378070.3067037142090752.00768674378924.368273686
#Sta/Elev= 30
       0 2958.22    71.2 2954.34     103 2943.61   155.7 2940.33   206.9 2943.52
   224.8  2943.4   235.5 2941.15   325.6 2944.18   375.5 2943.53   396.2  2940.2
   406.9 2941.91   417.6  2940.9   428.3  2943.2     514 2943.63   524.7  2941.2
     539 2943.19     614 2939.88   646.1 2941.82   663.9 2938.88   675.3 2941.37
   699.7 2958.42   712.8 2959.15   749.6 2969.77   778.2 2972.38   810.3 2985.52
   826.4 2989.55   860.3 3005.62   892.6  3029.1   925.1 3029.95   929.5 3031.97
#Mann= 3 ,-1 , 0
       0      .1       0   646.1    .045       0   675.3      .1       0
#XS Ineff= 2 , 0
           332.1 2948.58
Permanent Ineff=
       F       F
Bank Sta=646.1,675.3
XS Rating Curve= 0 ,0
Exp/Cntr=0.3,0.1