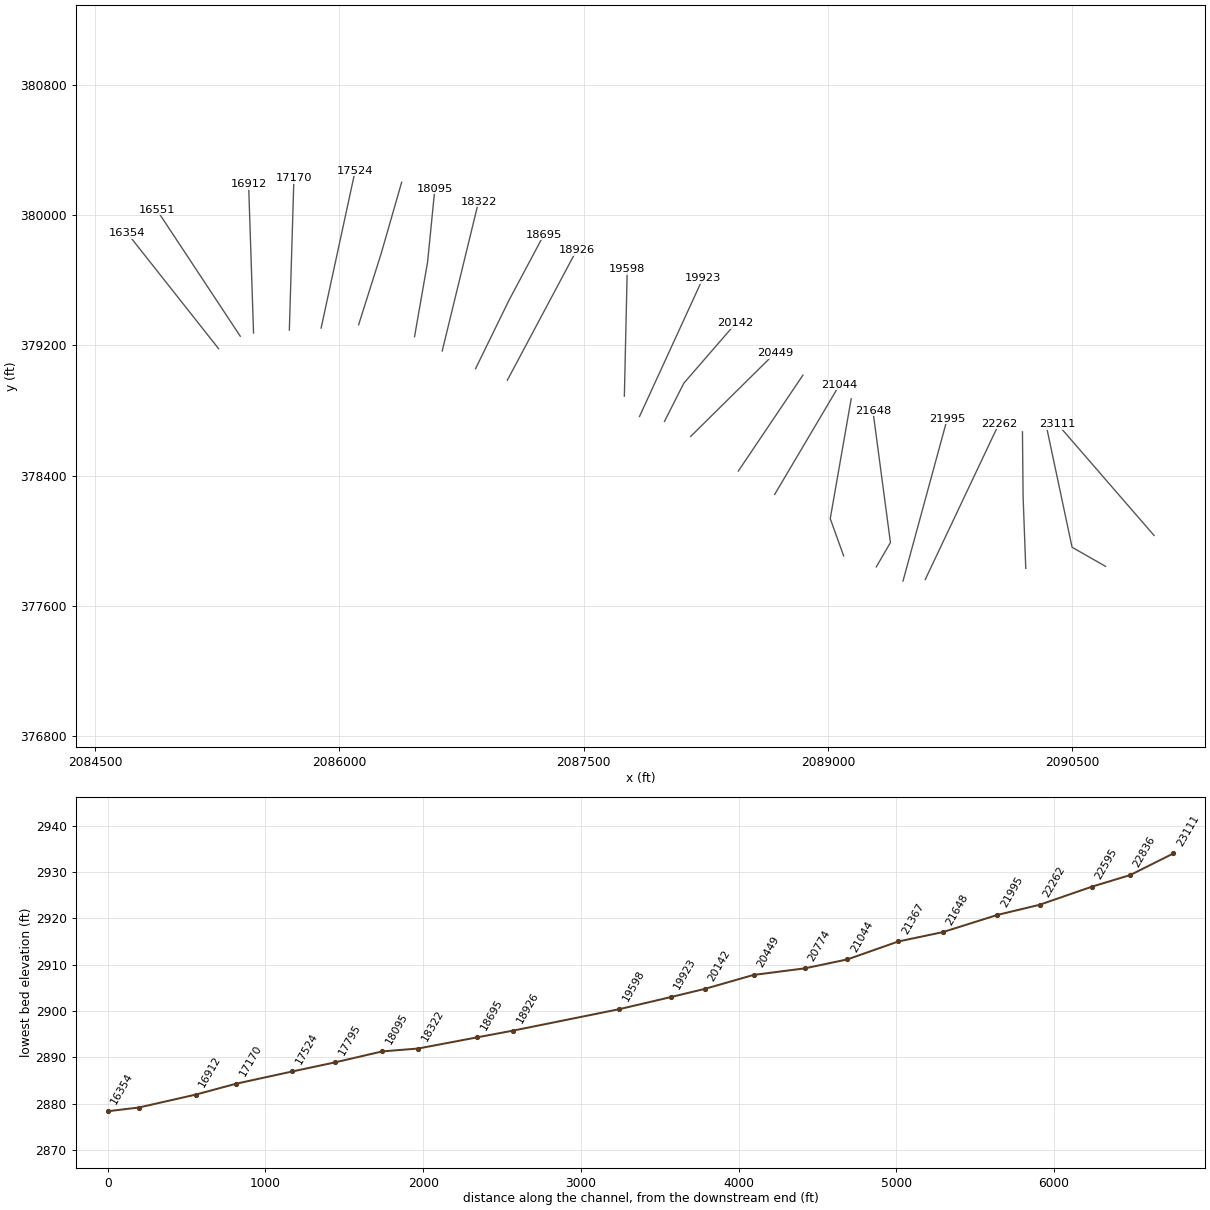
HEC-RAS study SFBIGCLRCK.prj: SFBIGCLRCK

--- SFBIGCLRCK.g01 (geometry) --- (continued)

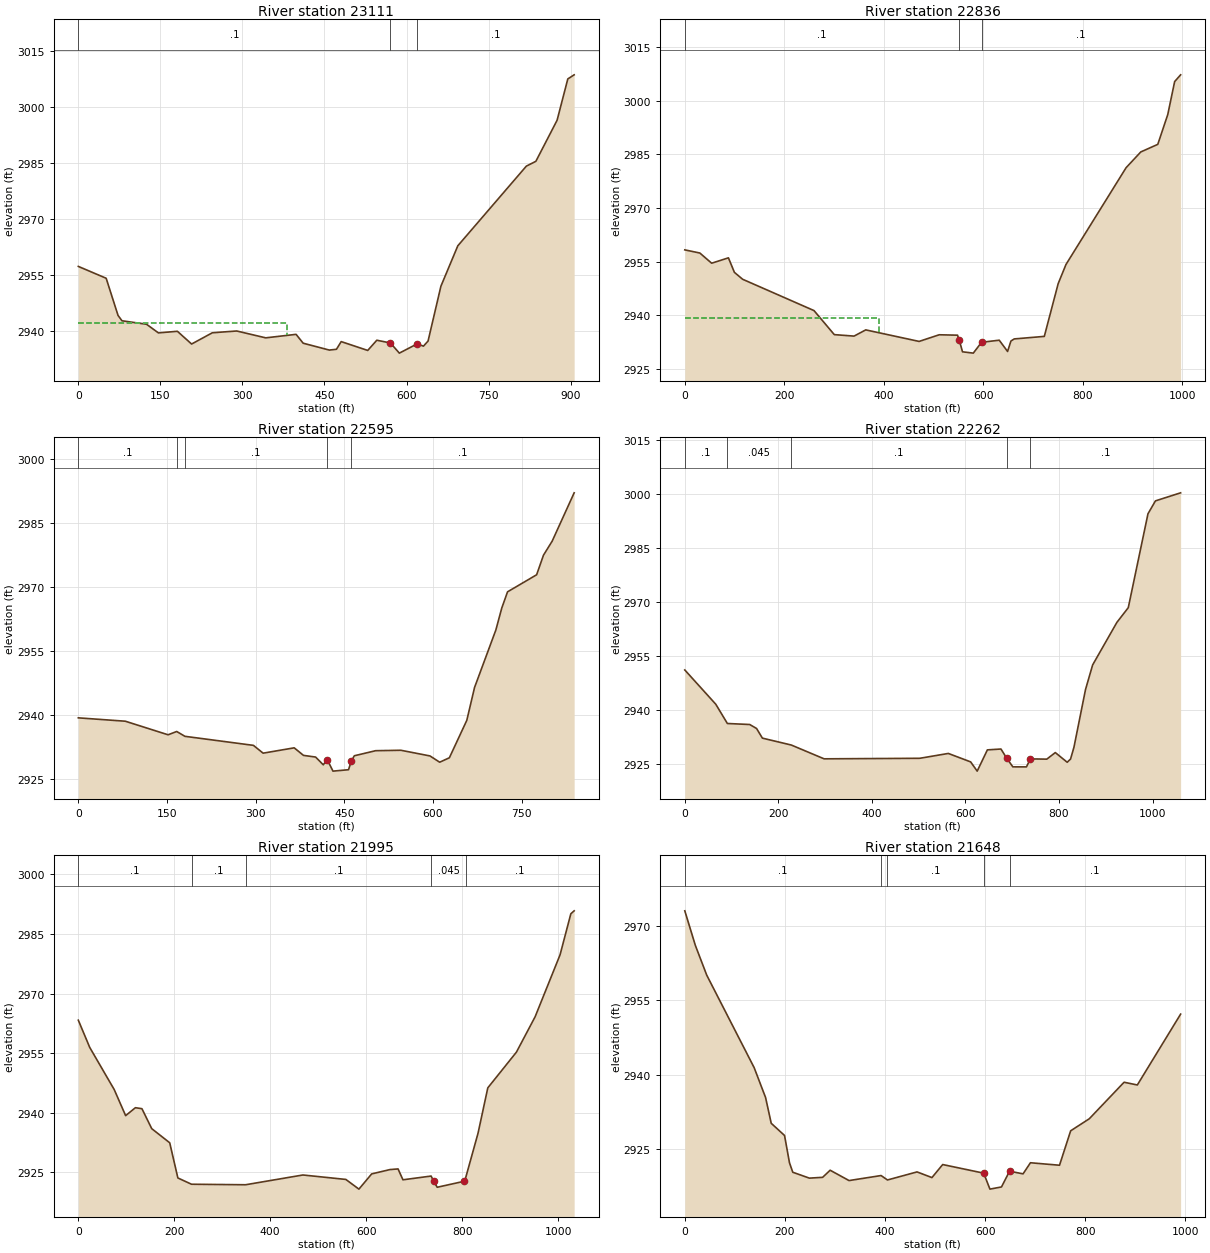
Type RM Length L Ch R = 1 ,23111   ,274.8,274.8,274.8
XS GIS Cut Line= 2
2091001.31002825378031.7050508342090407.80961522378716.884389455
#Sta/Elev= 30
       0 2957.29    50.9 2954.11    72.6 2944.14    79.8  2942.7   124.7 2941.77
   146.4 2939.45   181.1 2939.88   207.1 2936.46     245 2939.48   289.6 2939.96
   342.6 2938.12   398.1 2939.06   411.1 2936.68   458.9 2934.84   471.9 2935.05
   480.6 2937.11   529.1 2934.74   545.7 2937.48   570.6 2936.75   586.9 2934.02
   619.3 2936.49     631  2935.9   639.4 2937.26   662.9 2951.98   693.8 2962.82
   819.1  2984.2   836.5 2985.49   875.3 2996.51   894.9  3007.6   906.5  3008.7
#Mann= 3 ,-1 , 0
       0      .1       0   570.6    .045       0   619.3      .1       0
#XS Ineff= 2 , 0
          382.29 2942.19
Permanent Ineff=
       F       F
Bank Sta=570.6,619.3
XS Rating Curve= 0 ,0
Exp/Cntr=0.3,0.1

Type RM Length L Ch R = 1 ,22836   ,241.6,241.6,241.6
XS GIS Cut Line= 3
2090703.75562064 377841.913590842090497.88013861377959.326951683
2090340.25672268378702.408769625
#Sta/Elev= 30
       0 2958.27    30.3 2957.38      54 2954.53    87.7 2956.04    99.7 2951.97
   116.3 2950.03   259.7 2941.26   300.5 2934.52   340.2 2934.11   363.7 2935.85
     471 2932.62   511.3 2934.48   548.2 2934.37   551.5 2933.07   558.2 2929.71
   579.9 2929.34   596.5 2932.38     632 2932.96   648.8 2929.81   655.5 2932.72
   662.2 2933.32   722.6 2934.03   750.5 2948.81   766.2 2954.18     887 2981.29
   916.5  2985.7   950.7 2987.83   970.8  2996.2   984.6 3005.42   996.6 3007.31
#Mann= 3 ,-1 , 0
       0      .1       0   551.5    .045       0   596.5      .1       0
#XS Ineff= 2 , 0
          389.67 2939.09
Permanent Ineff=
       F       F
Bank Sta=551.5,596.5
XS Rating Curve= 0 ,0
Exp/Cntr=0.3,0.1

Type RM Length L Ch R = 1 ,22595   ,332.7,332.7,332.7
XS GIS Cut Line= 3
     2090213.597      377829.913     2090197.162         378274.
2090193.32888644378668.414050852
#Sta/Elev= 30
       0 2939.34    79.5 2938.55   151.8 2935.37  166.44 2936.14  180.33 2935.01
   296.2 2932.89   312.6 2931.06   365.2 2932.31   380.9 2930.54   401.4 2930.15
   414.4 2928.33     421 2929.56   430.8 2926.85   457.1 2927.18   461.9 2929.23
   466.9 2930.45     503 2931.64   545.7 2931.74   594.9 2930.41   611.3 2928.94
   627.7 2929.98   657.2 2938.76   670.3 2946.46   706.4 2959.96   716.3 2965.06
   726.1 2968.88   775.3 2972.88   786.9 2977.47   801.6 2980.76   838.8 2992.09
#Mann= 5 ,-1 , 0
       0      .1       0  166.44    .045       0  180.33      .1       0
     421    .045       0   461.9      .1       0
Bank Sta=421,461.9
XS Rating Curve= 0 ,0
Exp/Cntr=0.3,0.1

Type RM Length L Ch R = 1 ,22262   ,266.5,266.5,266.5
XS GIS Cut Line= 2
2089596.40284587377760.9105077232090049.48974655378719.196540471
#Sta/Elev= 30
       0 2951.07    66.3 2941.53   91.02 2936.18   138.8  2935.9   153.4  2934.8
   165.9 2932.11  227.68 2930.19   297.8 2926.35   502.4  2926.5   563.4 2927.85
   611.1  2925.5   625.1 2922.93   646.9 2928.84   675.9 2929.08   687.9 2926.59
   701.3 2924.12   730.4 2924.11   738.9 2926.34   773.9 2926.26   792.1 2928.09
   817.5  2925.4   824.7 2926.29     832  2929.6   856.7 2945.64   871.9 2952.47
   923.7  2964.3   948.1  2968.4   990.2 2994.52  1006.2 2998.11    1060 3000.35
#Mann= 5 ,-1 , 0
       0      .1       0   91.02    .045       0  227.68      .1       0
   687.9    .045       0   738.9      .1       0
Bank Sta=687.9,738.9
XS Rating Curve= 0 ,0
Exp/Cntr=0.3,0.1

Type RM Length L Ch R = 1 ,21995   ,347.6,347.6,347.6
XS GIS Cut Line= 2
2089459.96883828377751.8914971682089731.78881065378749.100863237
#Sta/Elev= 30
       0 2963.28    23.8 2956.42    74.8 2945.82    98.6 2939.25     119 2941.25
   132.6    2941     153 2935.98   190.5 2932.42   207.5 2923.56  235.96 2921.98
  348.63 2921.85   468.2 2924.31   557.7 2923.19   584.9 2920.75   611.5 2924.58
   649.5 2925.67   666.5 2925.84   676.7  2923.1   735.4 2924.04   740.8 2922.75
   748.1 2921.22   804.9 2922.74   807.8 2923.76   833.2 2934.81   853.6 2946.25
   913.3 2955.25   952.2 2964.14  1004.2 2979.74  1026.7 2990.08  1033.6 2990.82
#Mann= 5 ,-1 , 0
       0      .1       0  235.96      .1       0  348.63      .1       0
   735.4    .045       0   807.8      .1       0
Bank Sta=740.8,804.9
XS Rating Curve= 0 ,0
Exp/Cntr=0.3,0.1

Type RM Length L Ch R = 1 ,21648   ,280.9,280.9,280.9
XS GIS Cut Line= 3
2089295.91181354377838.7452161482089382.76553252377988.326621058
 2089275.0025849 378798.96133154
#Sta/Elev= 30
       0 2972.96      21 2966.04    43.8 2960.04   138.6 2941.44   161.4 2935.44
   172.7 2930.26   199.3 2927.81   209.2 2922.31   215.8 2920.42   248.9 2919.24
   275.4  2919.4   290.4 2920.83   328.2 2918.75  392.16 2919.76  404.99 2918.87
     464 2920.49   493.8 2919.35   515.3 2921.97   597.2 2920.24   609.7 2917.03
   632.8 2917.47   648.9 2920.63   675.9  2920.1   690.6 2922.33   748.7 2921.83
     771 2928.75   808.2 2931.17   877.7 2938.51   904.2 2937.96   990.7  2952.2
#Mann= 5 ,-1 , 0
       0      .1       0  392.16      .1       0  404.99      .1       0
   597.2    .045       0   648.9      .1       0
Bank Sta=597.2,648.9
XS Rating Curve= 0 ,0
Exp/Cntr=0.3,0.1

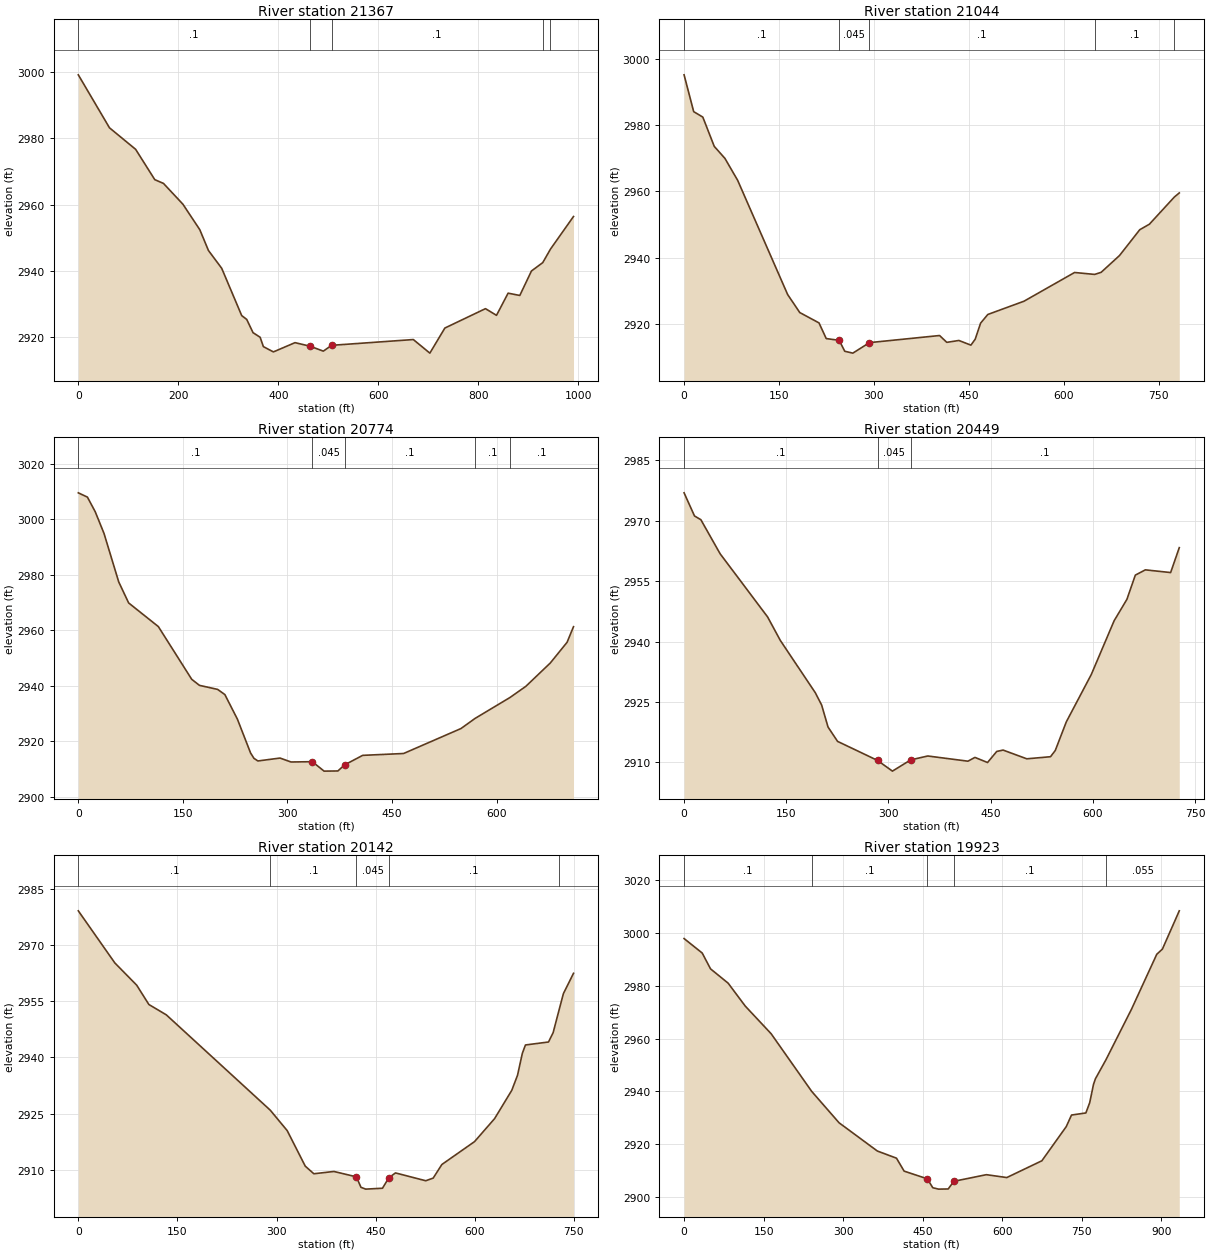
Type RM Length L Ch R = 1 ,21367   ,323.4,323.4,323.4
XS GIS Cut Line= 3
2089095.44949849377906.4768200442089013.24227476 378135.22735563
2089141.91445103378871.518142046
#Sta/Elev= 30
       0 2999.25    62.4 2983.21   114.7  2976.7     153 2967.52   170.4 2966.38
   209.2  2960.1   243.1 2952.36   260.3 2946.09   286.9 2940.68   326.8 2926.39
   336.9 2925.22   349.5 2921.22   363.7 2919.82   370.2 2916.99   390.2 2915.39
   433.5 2918.19   463.4 2917.12   490.1 2915.62   506.7 2917.38   670.1 2919.13
   703.2 2915.02   733.2 2922.61   814.4 2928.48   836.5 2926.46   859.7 2933.17
   883.1 2932.47   906.4 2939.88  928.99 2942.41  944.45  2946.5   990.5 2956.37
#Mann= 5 ,-1 , 0
       0      .1       0   463.4    .045       0   506.7      .1       0
  928.99      .1       0  944.45      .1       0
Bank Sta=463.4,506.7
XS Rating Curve= 0 ,0
Exp/Cntr=0.3,0.1

Type RM Length L Ch R = 1 ,21044   ,269.2,269.2,269.2
XS GIS Cut Line= 2
2088671.90358494378283.5577810492089070.42990866378957.299592891
#Sta/Elev= 30
       0 2995.12    15.2 2984.01    29.6 2982.37    47.7 2973.53    64.6  2969.9
    84.7 2963.29   163.7 2928.84   182.9 2923.39   213.3 2920.27   224.7 2915.54
   245.2 2915.01     254 2911.71   266.8 2911.15   293.1 2914.32   403.9 2916.46
   415.3  2914.4   434.4 2914.97   453.4 2913.56   460.2 2915.35   468.7 2920.18
   480.1 2922.81   537.3 2926.81   617.3 2935.48  648.99  2934.9   659.3 2935.53
   688.3 2940.59   720.3 2948.38   735.5 2950.04  775.03 2958.25   782.8 2959.49
#Mann= 5 ,-1 , 0
       0      .1       0   245.2    .045       0   293.1      .1       0
  648.99      .1       0  775.03      .1       0
Bank Sta=245.2,293.1
XS Rating Curve= 0 ,0
Exp/Cntr=0.3,0.1

Type RM Length L Ch R = 1 ,20774   ,325.2,325.2,325.2
XS GIS Cut Line= 2
 2088448.8003282378427.3131957562088845.43231155379016.470922838
#Sta/Elev= 30
       0 3009.49    13.1 3007.94    24.3 3002.66    36.8 2994.92      58 2977.38
    72.2 2969.82   114.8  2961.3   162.7 2942.29   173.8 2940.12   199.8 2938.67
   210.2  2936.8   228.2 2927.94   247.1 2915.75   251.9 2913.83   257.6 2912.88
   289.3 2913.93   305.1 2912.51   335.6 2912.62   352.5 2909.22   372.3 2909.28
   381.9 2911.46   407.8  2914.9   466.5 2915.57   548.8 2924.56  568.93 2928.19
  619.19 2935.76   641.9 2939.78   676.9 2948.17     701 2955.64   710.2 2961.26
#Mann= 5 ,-1 , 0
       0      .1       0   335.6    .045       0   381.9      .1       0
  568.93      .1       0  619.19      .1       0
Bank Sta=335.6,381.9
XS Rating Curve= 0 ,0
Exp/Cntr=0.3,0.1

Type RM Length L Ch R = 1 ,20449   ,307,307,307
XS GIS Cut Line= 2
2088156.39280764378640.1048072572088673.17243557379151.094187258
#Sta/Elev= 30
       0 2976.95    15.3  2971.2    24.6 2970.28    52.9 2961.81   122.6 2946.11
   141.3 2940.26   192.6 2927.28   201.9 2924.22   211.3 2918.75   225.3 2915.19
   283.9 2910.46   305.8  2907.8   332.6 2910.59   357.7 2911.56   416.6 2910.27
   426.9 2911.21   445.4 2909.94   458.9 2912.69   468.2 2913.03     503 2910.86
   537.8 2911.38   544.8 2912.93     561 2920.04   597.7 2931.82   631.2 2945.17
   649.9 2950.47   662.3  2956.5     677 2957.81   714.1 2957.14   726.8 2963.33
#Mann= 3 ,-1 , 0
       0      .1       0   283.9    .045       0   332.6      .1       0
Bank Sta=283.9,332.6
XS Rating Curve= 0 ,0
Exp/Cntr=0.3,0.1

Type RM Length L Ch R = 1 ,20142   ,219,219,219
XS GIS Cut Line= 3
2087995.71342752 378732.748774172088114.41351013378967.253815416
2088432.87714639379334.934559099
#Sta/Elev= 30
       0  2979.2    55.3 2965.27    88.4 2959.32   106.8 2954.16   133.2 2951.39
  290.42 2925.92   316.1 2920.45   343.4 2910.96   356.4 2908.92   386.8 2909.53
   420.8 2908.09   427.7  2905.3   434.9 2904.81   460.3 2905.05     470 2907.89
     480 2909.14   525.7 2907.05     537 2907.76   550.1 2911.39   599.5  2917.5
   629.9 2923.65   655.9 2931.22   664.6 2935.24   671.9 2941.12   676.6 2943.34
   711.5 2944.14   718.5 2946.64  726.61 2952.12     734 2957.06   749.3  2962.5
#Mann= 5 ,-1 , 0
       0      .1       0  290.42      .1       0   420.8    .045       0
     470      .1       0  726.61    .055       0
Bank Sta=420.8,470
XS Rating Curve= 0 ,0
Exp/Cntr=0.3,0.1

Type RM Length L Ch R = 1 ,19923   ,310.2,324.7,328.6
XS GIS Cut Line= 2
     2087842.073      378762.371      2088231.43      379611.602
#Sta/Elev= 30
       0 2997.89    34.2 2992.41    49.9 2986.42    83.1    2981   115.5  2972.3
   164.2 2961.86  240.642940.051   292.4 2928.13   364.6 2917.44   400.7 2914.73
   415.1 2909.83   458.8 2906.92   469.2 2903.54   480.1 2903.01   498.3 2903.07
   508.9 2905.97   570.3 2908.48   608.8 2907.39     675 2913.75     721 2926.69
   730.9 2931.06     758 2931.86   765.2 2935.72   772.4 2942.68     776 2944.79
  795.982952.042   844.3 2971.23   891.7 2991.93   902.4 2993.91   934.2 3008.39
#Mann= 5 ,-1 , 0
       0      .1       0  240.64      .1       0   458.8    .045       0
   508.9      .1       0  795.98    .055       0
Bank Sta=458.8,508.9
XS Rating Curve= 0 ,0
Exp/Cntr=0.3,0.1

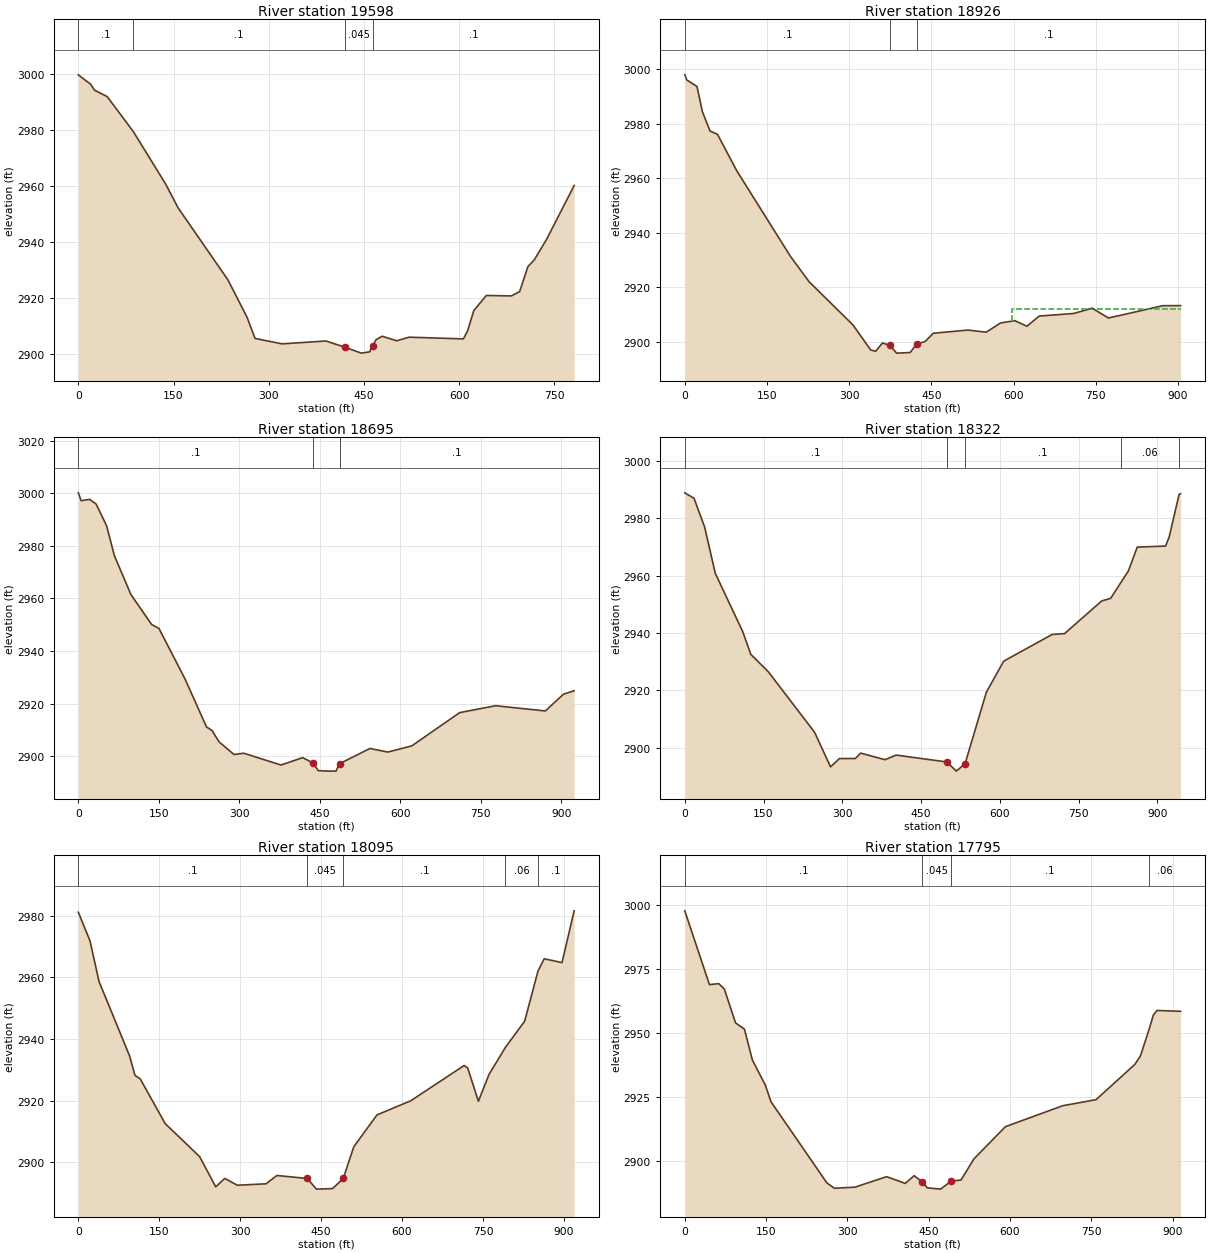
Type RM Length L Ch R = 1 ,19598   ,665.8,672.9,644.3
XS GIS Cut Line= 2
2087749.26379581378887.579090458 2087766.8516739379668.480877809
#Sta/Elev= 30
       0 2999.55    19.2 2996.23    25.8 2994.04    45.4 2991.81   86.542979.369
   137.3 2960.76     157 2952.23   235.8 2926.47     266 2913.09   278.4 2905.66
   321.1 2903.72     390 2904.75   419.6 2902.55   445.8 2900.42   458.9 2900.89
     464 2903.12   468.8 2905.18   478.6 2906.44   501.6 2904.82   521.1  2906.1
   606.6 2905.49   613.2 2908.31     623 2915.58   642.7 2920.96   682.1 2920.79
   695.2 2922.33   708.3 2931.28   718.2 2933.61   737.9 2941.05   781.1 2960.11
#Mann= 4 ,-1 , 0
       0      .1       0   86.54      .1       0   419.6    .045       0
     464      .1       0
Bank Sta=419.6,464
XS Rating Curve= 0 ,0
Exp/Cntr=0.3,0.1

Type RM Length L Ch R = 1 ,18926   ,226.9,230.8,228
XS GIS Cut Line= 2
2087030.86737399378985.5708618842087456.08672562 379784.09324896
#Sta/Elev= 30
       0 2998.04     3.6 2996.17    22.2 2993.77    32.1 2984.53      46 2977.39
    59.6 2976.18    94.9 2962.77   192.6 2931.39   226.7 2922.05     307 2906.11
   339.2 2896.94   348.2 2896.46   360.8 2899.54   374.1 2898.62   386.5 2895.79
   411.3 2896.01     423 2899.13   438.5 2900.06   453.4 2903.09   516.6 2904.27
     550 2903.48   576.2 2906.88   602.1 2907.72   624.4 2905.67   646.7 2909.41
   709.6 2910.35   743.3 2912.31   773.1 2908.69   872.1 2913.21   904.7 2913.25
#Mann= 3 ,-1 , 0
       0      .1       0   374.1    .045       0     423      .1       0
#XS Ineff= 2 , 0
                          596.85         2912.18
Permanent Ineff=
       F       F
Bank Sta=374.1,423
XS Rating Curve= 0 ,0
Exp/Cntr=0.3,0.1

Type RM Length L Ch R = 1 ,18695   ,372.7,372.7,372.7
XS GIS Cut Line= 3
     2086835.682      379056.321     2087040.753      379476.255
     2087255.265      379879.086
#Sta/Elev= 30
       0 3000.15     5.2 2997.16    20.9 2997.68    33.1 2995.89    52.6 2987.68
    67.2 2976.23    97.9  2961.5   136.6 2950.07   150.2 2948.58   198.7  2929.4
   238.8 2911.12     249 2909.79   262.3 2905.41     290 2900.64   308.2 2901.13
   377.6 2896.64   417.8 2899.44   437.6  2897.4     447  2894.5   464.9 2894.32
     480 2894.33   486.7 2897.14   543.2 2902.93   576.7 2901.57   621.3 2903.93
   710.5 2916.58   777.4 2919.19     870  2917.2   903.9 2923.58   923.7 2924.89
#Mann= 3 ,-1 , 0
       0      .1       0   437.6    .045       0   486.7      .1       0
Bank Sta=437.6,486.7
XS Rating Curve= 0 ,0
Exp/Cntr=0.3,0.1

Type RM Length L Ch R = 1 ,18322   ,227.3,227.3,227.3
XS GIS Cut Line= 2
2086631.03232433379165.2901188522086854.25754289 380082.79849748
#Sta/Elev= 30
       0 2988.78    17.6 2986.88    37.8 2976.85    58.1 2960.75   110.5 2940.41
   125.6  2932.6   159.4 2926.43   247.2 2905.43   277.6 2893.39   294.4 2896.29
   324.8 2896.31     335 2898.19   381.2  2895.9   402.5  2897.5   498.6 2895.12
   517.3 2891.92   533.9 2894.56   574.4 2919.41   607.4  2930.2   699.6 2939.48
   723.3 2939.79   794.2 2951.17   811.1 2952.05  830.97  2957.7   844.8 2961.58
   861.7 2969.89   915.7 2970.25   922.5 2973.41  941.34 2988.21   944.3 2988.49
#Mann= 5 ,-1 , 0
       0      .1       0   498.6    .045       0   533.9      .1       0
  830.97     .06       0  941.34    .055       0
Bank Sta=498.6,533.9
XS Rating Curve= 0 ,0
Exp/Cntr=0.3,0.1

Type RM Length L Ch R = 1 ,18095   ,300,300,300
XS GIS Cut Line= 3
     2086461.148      379252.931     2086541.293      379712.183
     2086585.891      380162.791
#Sta/Elev= 30
       0  2981.1    21.6 2971.84    38.3 2958.67    94.9 2934.54   104.9 2928.22
   114.9 2927.01   160.9 2912.57   224.8 2901.85   254.7 2892.04   271.4 2894.78
   294.7 2892.56     348 2893.03     368 2895.72   424.6 2894.75   441.2  2891.3
   471.2 2891.47     491 2894.76   510.7 2905.09   553.6 2915.37   616.2 2919.96
   715.1 2931.39   721.7 2930.58   741.5 2919.81   761.3 2928.53  791.54 2937.26
   827.2 2945.73  851.95    2962   863.5 2966.01   896.5 2964.77     919 2981.56
#Mann= 5 ,-1 , 0
       0      .1       0   424.6    .045       0     491      .1       0
  791.54     .06       0  851.95      .1       0
Bank Sta=424.6,491
XS Rating Curve= 0 ,0
Exp/Cntr=0.3,0.1

Type RM Length L Ch R = 1 ,17795   ,270.4,270.4,270.4
XS GIS Cut Line= 3
     2086117.823      379326.022     2086255.817      379762.424
     2086382.067      380201.784
#Sta/Elev= 30
       0 2997.73    45.5 2968.87    62.7 2969.27      73 2967.13    93.6 2953.93
   110.1 2951.47   124.6 2939.45   148.7 2929.54     159  2923.1   262.2 2891.35
     276 2889.27   313.9  2889.7   372.4  2893.8   406.8 2891.17   423.2 2894.19
   437.7 2891.75   447.3 2889.44     472 2888.93   491.3 2892.03   509.6 2892.49
   533.5 2900.75   591.5 2913.34   697.3 2921.54   758.8  2923.9   830.5 2937.73
   840.7 2941.03  855.88 2950.91   864.6 2957.03   871.4 2958.78   914.8 2958.44
#Mann= 4 ,-1 , 0
       0      .1       0   437.7    .045       0   491.3      .1       0
  855.88     .06       0
Bank Sta=437.7,491.3
XS Rating Curve= 0 ,0
Exp/Cntr=0.3,0.1

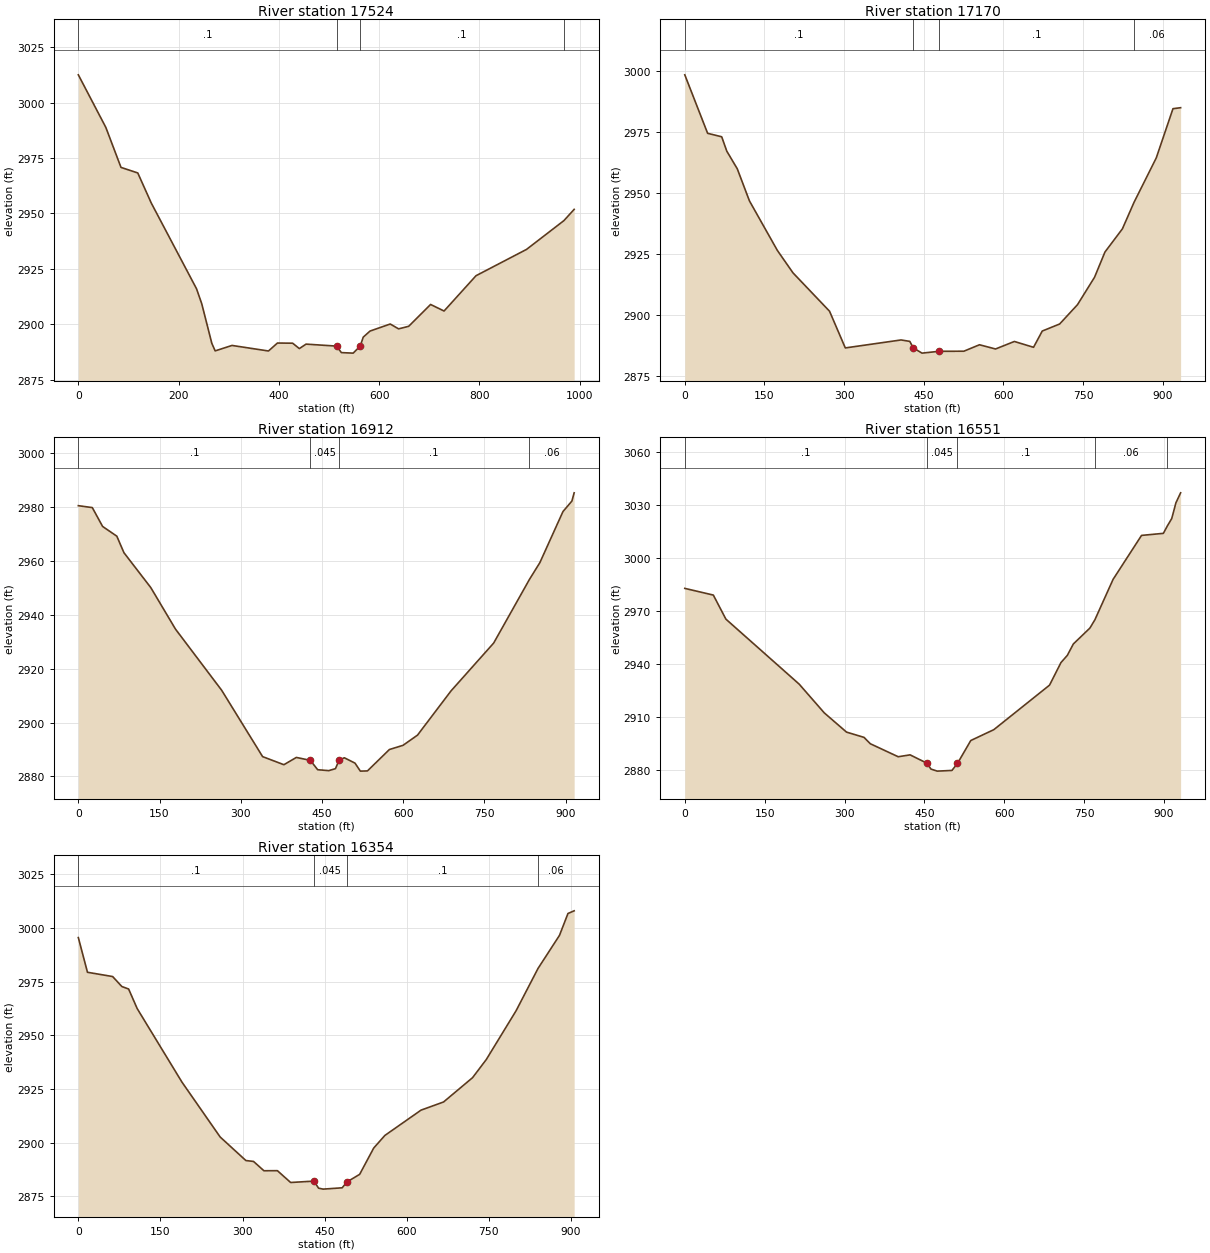
Type RM Length L Ch R = 1 ,17524   ,354.6,354.6,354.6
XS GIS Cut Line= 2
2085887.53415545379305.9044297532086096.69794291380272.627817196
#Sta/Elev= 30
       0 3012.49    54.9 2988.76    85.1 2970.74   118.6 2968.23   145.5 2954.67
   235.8 2915.99   246.2 2909.25   266.3 2891.38     273 2887.98   306.6 2890.44
   379.3 2887.93   397.2 2891.52   427.5 2891.45   440.9 2889.02   454.3 2891.03
   515.1 2890.14   524.8  2887.2   548.3 2886.97   562.3 2890.16   568.4 2894.19
   581.9 2896.92   622.2  2900.1   638.9 2897.91   659.1 2899.08   702.7 2908.92
   729.6 2905.96   793.3 2921.88     894 2933.74  968.69 2946.74   989.1 2951.81
#Mann= 4 ,-1 , 0
       0      .1       0   515.1    .045       0   562.3      .1       0
  968.69     .06       0
Bank Sta=515.1,562.3
XS Rating Curve= 0 ,0
Exp/Cntr=0.3,0.1

Type RM Length L Ch R = 1 ,17170   ,257.5,257.5,257.5
XS GIS Cut Line= 2
2085692.43179907379293.6006775492085720.55466125380226.928166154
#Sta/Elev= 30
       0 2998.44      43 2974.46    69.5 2973.04    79.1 2967.14    98.8 2959.93
   121.8 2946.73   174.3 2926.46   203.8 2917.24   272.6 2901.52   302.3 2886.47
   407.3 2889.74   423.7 2889.16   430.3 2886.48   446.7 2884.34     479 2885.09
   525.5 2885.12     555 2887.77   585.2 2886.04   620.7 2889.12   656.8 2886.73
   673.2 2893.39     706 2896.29   739.6 2904.21   771.7 2915.45   791.3 2925.79
   824.2 2935.31  845.81 2946.05   887.9 2964.36   919.4 2984.55   933.8 2984.96
#Mann= 4 ,-1 , 0
       0      .1       0   430.3    .045       0     479      .1       0
  845.81     .06       0
Bank Sta=430.3,479
XS Rating Curve= 0 ,0
Exp/Cntr=0.3,0.1

Type RM Length L Ch R = 1 ,16912   ,361.2,361.2,361.2
XS GIS Cut Line= 2
     2085472.677      379275.388     2085442.315       380190.52
#Sta/Elev= 30
       0 2980.48    25.8 2979.77    44.8 2972.78    71.1 2969.16    84.2 2963.04
   133.8 2950.09   179.4 2934.68   264.7 2911.98   340.3 2887.36   379.6 2884.36
   402.6 2887.06   428.4 2885.98     442  2882.5   462.4 2882.16   474.8 2882.89
   481.4 2885.99   491.2 2886.94   510.9 2884.95   520.8 2881.98   533.9 2882.06
   574.4 2889.99   599.6 2891.56   626.3 2895.33   688.2 2911.74     767 2929.51
   832.9 2953.07   852.3 2959.35     895 2978.32   911.4 2982.18   915.6 2985.25
#Mann= 4 ,-1 , 0
       0      .1       0   428.4    .045       0   481.4      .1       0
   832.9     .06       0
Bank Sta=428.4,481.4
XS Rating Curve= 0 ,0
Exp/Cntr=0.3,0.1

Type RM Length L Ch R = 1 ,16551   ,196.6,196.6,196.6
XS GIS Cut Line= 2
     2085391.196      379255.749     2084878.189      380032.924
#Sta/Elev= 30
       0 2982.88    53.6 2979.08    77.2 2965.42   214.8 2928.55   261.9 2912.26
   303.7 2901.33   336.6 2898.34   348.4 2894.73   400.8 2887.35   423.1 2888.42
   454.6 2883.72   462.4 2880.34   474.2 2879.19   501.7 2879.58   512.1 2883.56
   537.1 2896.55   580.4 2902.72     685 2927.97   706.5 2940.79   718.4 2944.85
   729.7 2951.33   760.8 2960.35   770.2 2965.07   804.4    2988   857.8 3012.93
   898.8  3014.1  906.26 3018.29   914.5 3022.49   922.4 3031.44   931.2 3037.09
#Mann= 5 ,-1 , 0
       0      .1       0   454.6    .045       0   512.1      .1       0
   770.2     .06       0  906.26      .1       0
Bank Sta=454.6,512.1
XS Rating Curve= 0 ,0
Exp/Cntr=0.3,0.1

Type RM Length L Ch R = 1 ,16354   ,414.3,414.3,414.3
XS GIS Cut Line= 2
2085258.11541027379179.1255827442084696.61594347379890.081469545
#Sta/Elev= 30
       0 2995.47    16.7 2979.32    62.7 2977.33    79.5 2972.69    91.9 2971.52
   107.6 2962.39   189.3 2928.21   259.1 2902.66   306.1  2891.7   320.1 2891.28
   339.1 2886.94   363.7 2886.98   387.9 2881.48   430.5 2882.12   438.9 2878.84
   447.3 2878.39   482.1 2879.01   490.7 2881.71     514 2885.27   539.7 2897.52
   560.1 2903.38   626.1 2915.15   667.3 2918.95   720.3 2930.27   745.3 2938.68
   799.7 2961.36  839.86 2981.09   879.1  2996.5   894.6 3006.68   905.9 3007.92
#Mann= 4 ,-1 , 0
       0      .1       0   430.5    .045       0   490.7      .1       0
  839.86     .06       0
Bank Sta=430.5,490.7
XS Rating Curve= 0 ,0
Exp/Cntr=0.3,0.1