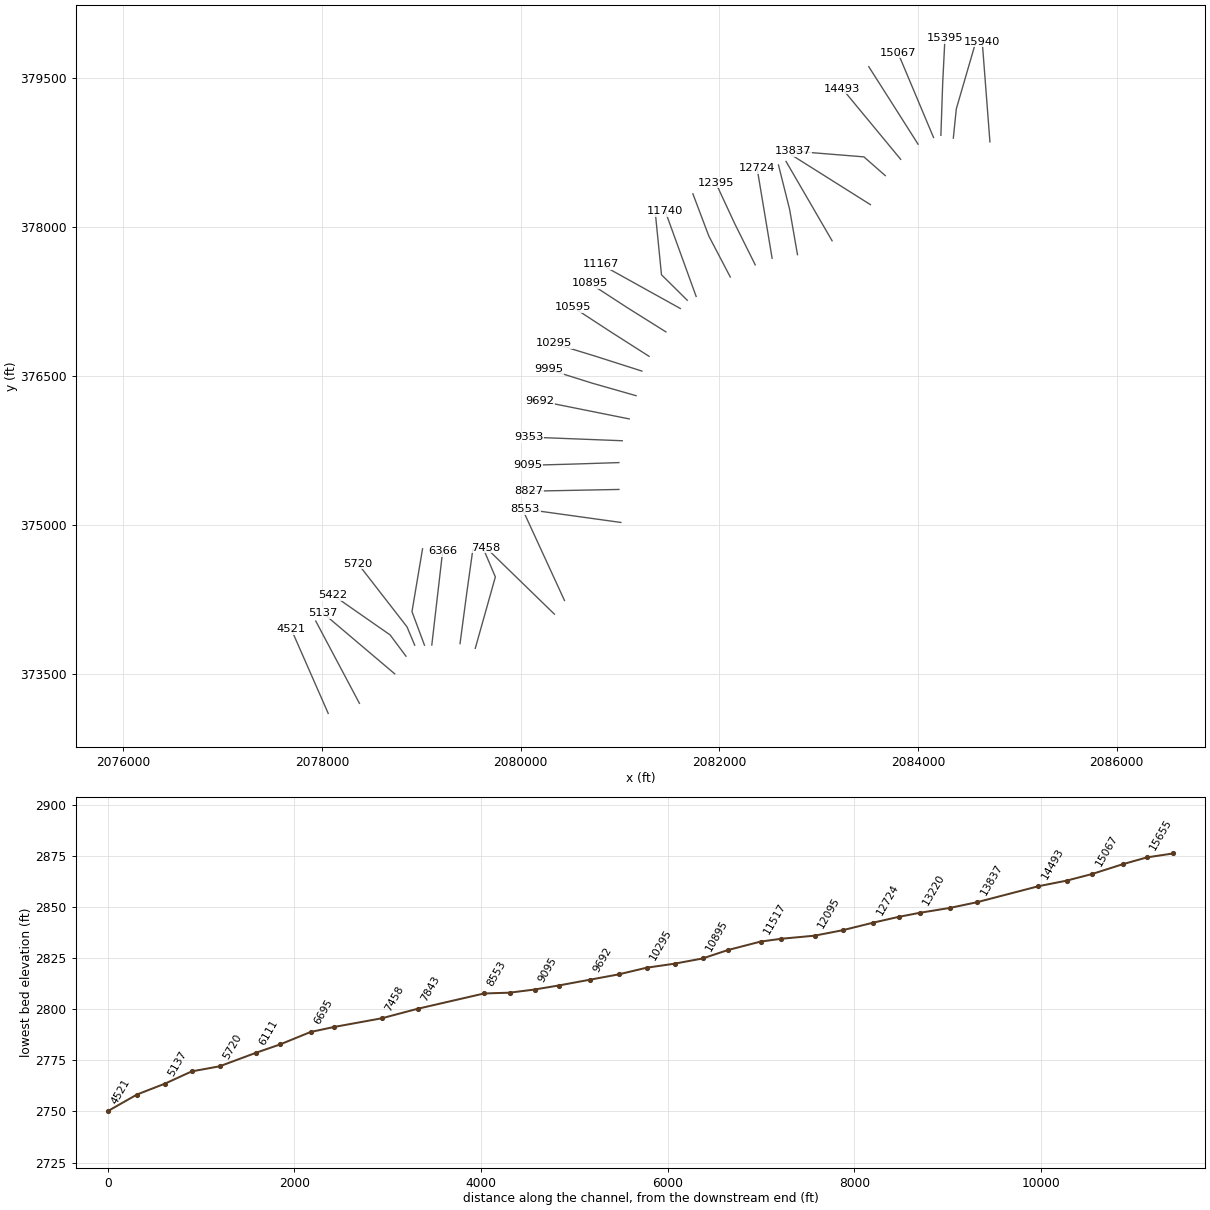
HEC-RAS study SFBIGCLRCK.prj: SFBIGCLRCK

--- SFBIGCLRCK.g01 (geometry) --- (continued)

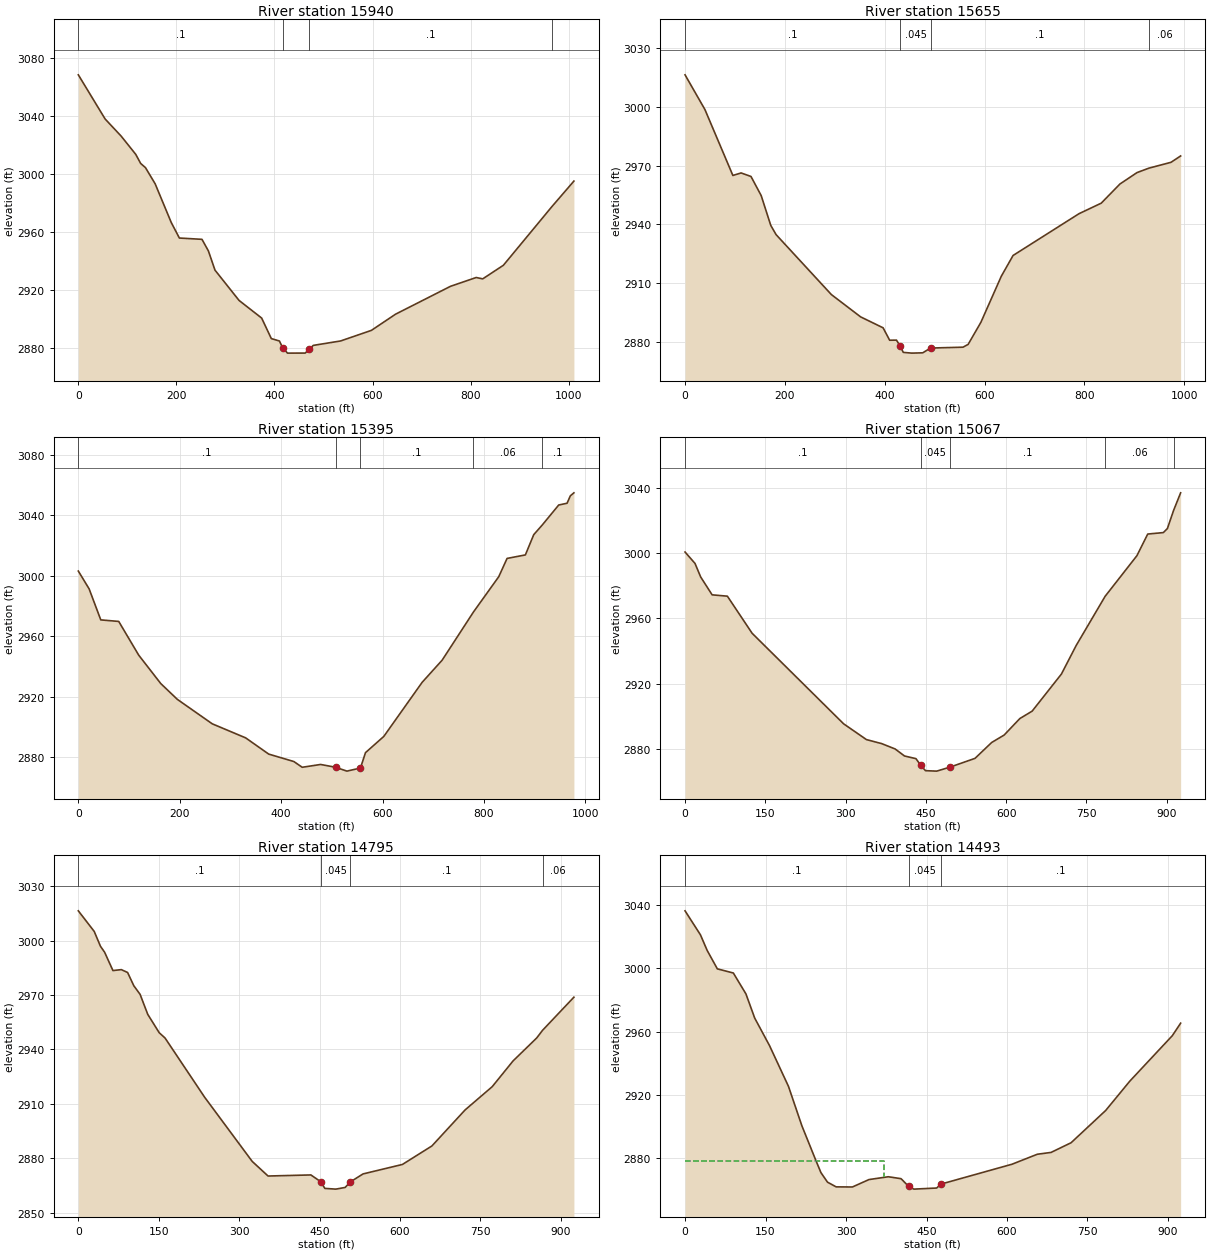
Type RM Length L Ch R = 1 ,15940   ,285.6,285.6,285.6
XS GIS Cut Line= 2
2084724.55549731378852.2064322532084647.04185843379859.883737747
#Sta/Elev= 30
       0 3068.64    54.7  3038.1    87.6 3026.18   117.2 3013.62   127.1  3007.4
     137 3004.46   156.7 2993.31   189.6  2966.5   206.1 2955.81   252.2 2954.92
   265.3 2946.89   278.7 2933.64   327.8 2912.68   373.9 2900.48   393.6  2886.3
   410.1 2884.63   416.7 2880.01   426.6 2876.25   462.7 2876.28   471.2 2879.01
   479.2  2881.6   534.9 2884.66   597.7 2891.98     647 2903.17   758.9 2922.42
   811.5 2928.54   824.7 2927.58   866.9 2936.99  965.95 2977.59  1010.7 2995.18
#Mann= 4 ,-1 , 0
       0      .1       0   416.7    .045       0   471.2      .1       0
  965.95     .06       0
Bank Sta=416.7,471.2
XS Rating Curve= 0 ,0
Exp/Cntr=0.3,0.1

Type RM Length L Ch R = 1 ,15655   ,259.9,259.9,259.9
XS GIS Cut Line= 3
2084355.97023487378890.1722961962084386.02654382379184.407741756
2084580.60159653379853.556093756
#Sta/Elev= 30
       0 3016.27    39.8 2998.57    95.8 2964.93   112.3 2966.21   132.1 2964.41
   152.5 2954.67   171.7 2939.46   182.4 2934.73   293.1 2904.16   351.7 2892.78
   396.7  2887.2   409.8 2880.87   423.5 2880.93   431.1 2877.79   437.1 2874.67
   454.2 2874.29   476.1 2874.45   491.8 2876.88   556.7 2877.32     567 2878.75
   592.6 2890.04   633.5 2913.55     657 2924.11   789.1 2945.43   833.5 2950.78
   871.1 2960.58   905.2 2966.39  928.78 2968.64   973.3 2971.64   992.6 2974.88
#Mann= 4 ,-1 , 0
       0      .1       0   431.1    .045       0   491.8      .1       0
  928.78     .06       0
Bank Sta=431.1,491.8
XS Rating Curve= 0 ,0
Exp/Cntr=0.3,0.1

Type RM Length L Ch R = 1 ,15395   ,327.2,327.2,327.2
XS GIS Cut Line= 3
     2084230.793      378918.291     2084249.111      379447.534
     2084271.671      379894.702
#Sta/Elev= 30
       0 3003.12    21.3 2991.36    44.3 2970.86    79.7 2969.83   119.1 2947.56
   162.5 2928.82   195.3 2918.34   264.2 2902.17   329.9 2892.92   375.5 2882.18
   425.1 2877.26   441.5 2873.47   477.7 2875.33   507.2  2873.5   529.6 2870.93
   556.4 2872.99   566.3 2883.14   602.4 2893.85     678 2929.59   717.4 2944.21
  779.16 2976.04   829.1  2999.4   845.5 3011.47   881.6 3013.78   898.1 3027.18
  914.72 3033.48   947.3 3046.75   963.8 3047.93   970.3 3052.84   977.3 3054.81
#Mann= 5 ,-1 , 0
       0      .1       0   507.2    .045       0   556.4      .1       0
  779.16     .06       0  914.72      .1       0
Bank Sta=507.2,556.4
XS Rating Curve= 0 ,0
Exp/Cntr=0.3,0.1

Type RM Length L Ch R = 1 ,15067   ,272.8,272.8,272.8
XS GIS Cut Line= 2
     2084156.916      378896.216     2083798.137      379749.773
#Sta/Elev= 30
       0 3000.84    18.6 2993.84    29.2 2985.51    50.6 2974.53    79.1  2973.7
   125.3 2950.91   296.2 2895.26   338.9 2885.54   367.3 2883.08   392.5 2879.78
     410 2875.47   431.4 2873.83   440.1 2869.85   449.2 2866.44   470.2 2866.16
   495.5 2868.68   541.7    2874   572.9 2883.77   596.2 2888.34   625.5 2898.48
   648.5 2903.04   703.2 2925.84   730.7 2943.36  784.82 2973.61   844.2 2998.59
   864.4 3011.89   893.6 3012.79   901.2 3015.29  912.59 3026.29   925.9 3037.23
#Mann= 5 ,-1 , 0
       0      .1       0   440.1    .045       0   495.5      .1       0
  784.82     .06       0  912.59      .1       0
Bank Sta=440.1,495.5
XS Rating Curve= 0 ,0
Exp/Cntr=0.3,0.1

Type RM Length L Ch R = 1 ,14795   ,301.7,301.7,301.7
XS GIS Cut Line= 3
     2084000.892      378829.237     2083747.618      379227.923
     2083504.722      379609.456
#Sta/Elev= 30
       0 3016.49    29.7  3005.1    41.3 2996.95    49.1 2993.62    64.6 2983.52
    80.2 2984.04    91.9 2982.48   103.5 2975.16   115.3 2970.38   129.5 2959.39
   150.9 2949.24   161.8 2946.31   235.7 2913.62   324.4 2878.22     354 2870.15
   433.9 2870.75   452.8 2866.91   459.9 2863.32   480.5 2862.92   497.9 2863.86
   507.5  2866.9   531.2 2871.31   604.7 2876.54   659.7 2886.75   721.7 2906.65
   772.2 2919.46   811.1 2933.67   855.2 2946.33  866.01 2950.53   924.6 2968.84
#Mann= 4 ,-1 , 0
       0      .1       0   452.8    .045       0   507.5      .1       0
  866.01     .06       0
Bank Sta=452.8,507.5
XS Rating Curve= 0 ,0
Exp/Cntr=0.3,0.1

Type RM Length L Ch R = 1 ,14493   ,656.1,656.1,656.1
XS GIS Cut Line= 2
2083826.03005066378676.6143115152083237.55915954379388.474260451
#Sta/Elev= 30
       0 3036.51    28.7 3021.31    41.3 3011.38    60.2 2999.74      90 2997.12
   113.5 2983.87   129.8 2968.58   157.4 2951.14   192.8 2925.27   217.7 2900.35
     244 2878.21   253.3 2870.62   265.5  2864.6   281.6 2861.62   311.9 2861.55
   342.8 2866.25   378.8 2868.03   402.5 2866.81   416.5 2862.03   426.3 2860.19
   468.9 2860.89   477.1 2863.39   609.4 2875.97   656.5 2882.29   682.1 2883.44
   719.4 2889.57   783.9 2910.01   828.9 2928.61   908.2 2957.44   923.6 2965.33
#Mann= 3 ,-1 , 0
       0      .1       0   416.5    .045       0   477.1      .1       0
#XS Ineff= 2 , 0
          370.65 2878.15
Permanent Ineff=
       F       F
Bank Sta=416.5,477.1
XS Rating Curve= 0 ,0
Exp/Cntr=0.3,0.1

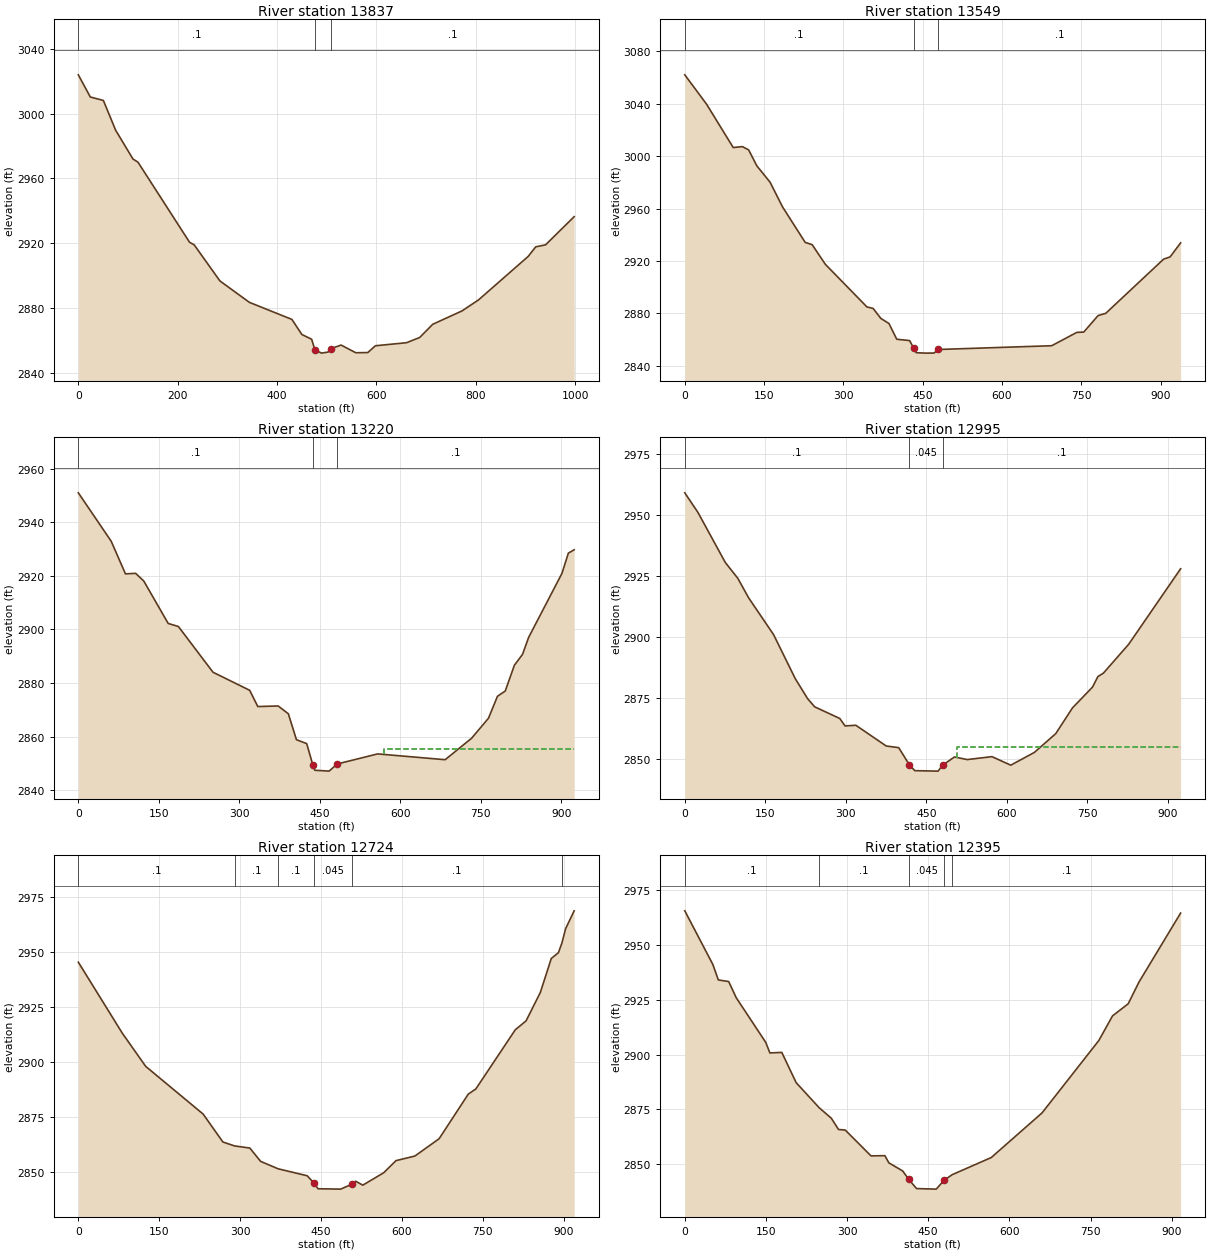
Type RM Length L Ch R = 1 ,13837   ,288,288,288
XS GIS Cut Line= 3
2083670.74581869378512.6245177132083455.91839926378701.412249941
2082746.40571113378758.725818474
#Sta/Elev= 30
       0 3023.83    24.1 3010.17    50.4 3008.05    75.2 2989.65     110 2971.95
     120 2970.03   223.8  2920.7   233.3 2919.04   284.9 2896.87   344.4 2883.64
   429.8 2873.16   449.8 2863.88   469.5 2860.94   476.1 2854.44   489.3 2852.39
   502.4 2853.04     509 2855.22   528.8 2857.35   558.4 2852.62   582.5 2852.75
   597.9 2856.93   660.4  2858.8   686.8 2861.99   713.1 2870.14   772.3 2878.42
   805.3 2885.16   905.3 2911.97   920.5 2917.87   940.2 2919.09   997.8 2936.44
#Mann= 3 ,-1 , 0
       0      .1       0   476.1    .045       0     509      .1       0
Bank Sta=476.1,509
XS Rating Curve= 0 ,0
Exp/Cntr=0.3,0.1

Type RM Length L Ch R = 1 ,13549   ,328.7,328.7,328.7
XS GIS Cut Line= 2
     2083521.108      378220.608     2082727.444      378720.525
#Sta/Elev= 30
       0 3062.12    41.2  3039.7    91.6 3006.61   108.9  3007.3   120.8 3004.81
   136.3 2992.62   161.4 2980.09     185 2961.22   227.8 2934.17     241 2932.42
   265.9 2917.43   344.4 2884.95   356.3 2883.74   370.8 2876.16   386.3 2872.21
     401 2860.21   425.3 2859.21   432.8 2853.61   437.9 2849.93   456.1 2849.62
   471.6  2849.7   479.4  2852.4   694.1 2855.27   741.7 2865.47   754.7 2865.67
   781.8 2878.28   796.4 2880.03   905.8 2921.37   918.1 2923.09     938 2933.82
#Mann= 3 ,-1 , 0
       0      .1       0   432.8    .045       0   479.4      .1       0
Bank Sta=432.8,479.4
XS Rating Curve= 0 ,0
Exp/Cntr=0.3,0.1

Type RM Length L Ch R = 1 ,13220   ,225.6,225.6,225.6
XS GIS Cut Line= 2
     2083135.633      377856.448     2082672.114      378655.265
#Sta/Elev= 30
       0 2950.94    61.2  2932.9    87.8 2920.72   106.7 2920.92   121.9 2918.06
   167.4 2902.23   186.4 2901.09   250.9 2884.04   319.2 2877.31   334.3 2871.25
   372.3 2871.46   391.2 2868.56   406.3 2858.89   425.4 2857.43   436.7 2849.57
   440.5  2847.5   467.1 2847.17   482.3 2849.84   557.5 2853.59   683.3 2851.43
   732.6 2859.44     764 2866.89   780.8 2875.09   795.2 2877.03   812.3 2886.67
   827.4  2890.7   838.8 2897.03   900.8 2920.88   912.8 2928.45   923.6 2929.71
#Mann= 3 ,-1 , 0
       0      .1       0   436.7    .045       0   482.3      .1       0
#XS Ineff= 2 , 0
                          569.18         2855.42
Permanent Ineff=
       F       F
Bank Sta=436.7,482.3
XS Rating Curve= 0 ,0
Exp/Cntr=0.3,0.1

Type RM Length L Ch R = 1 ,12995   ,270.4,270.4,270.4
XS GIS Cut Line= 3
     2082787.126      377716.874     2082707.866      378172.827
     2082595.574      378619.896
#Sta/Elev= 30
       0 2958.95    24.4 2950.97    75.5 2930.47    98.8    2924   118.8 2916.07
   165.4 2900.99   205.9 2882.95   228.8 2874.82     242 2871.47   288.7 2866.72
   298.6 2863.66   318.6 2863.94   375.2 2855.47   398.5 2854.78   418.5 2847.73
   428.5 2845.38   471.9 2845.19   480.2 2847.61   502.4 2850.98   526.1 2849.91
   572.2 2851.11   607.3 2847.62   651.2 2852.83   691.1 2860.52   722.3 2871.06
   759.5 2879.52   769.6 2883.85   779.8 2885.23   827.1 2897.09   923.7 2927.92
#Mann= 3 ,-1 , 0
       0      .1       0   418.5    .045       0   480.2      .1       0
#XS Ineff= 2 , 0
                          507.75         2855.13
Permanent Ineff=
       F       F
Bank Sta=418.5,480.2
XS Rating Curve= 0 ,0
Exp/Cntr=0.3,0.1

Type RM Length L Ch R = 1 ,12724   ,329.6,329.6,329.6
XS GIS Cut Line= 2
     2082531.577      377681.172     2082380.344      378587.796
#Sta/Elev= 30
       0  2945.5    81.7 2913.17   124.9 2898.16   231.4 2876.48     268  2863.8
  289.58 2862.01   317.9 2861.05     338 2854.99  370.22 2851.63   424.3 2848.45
   437.3 2845.01   444.3 2842.55   486.3 2842.38   507.4 2844.65   514.1 2845.98
   527.4 2844.19   566.1 2849.82   588.9 2855.33   623.9 2857.41   668.9 2865.29
   722.9 2885.54     737 2887.92   810.1 2914.79   830.1 2918.86   856.5 2931.74
   876.8 2947.19     890 2949.81  896.58 2954.26   903.3 2960.68   919.2 2968.84
#Mann= 6 ,-1 , 0
       0      .1       0  289.58      .1       0  370.22      .1       0
   437.3    .045       0   507.4      .1       0  896.58     .06       0
Bank Sta=437.3,507.4
XS Rating Curve= 0 ,0
Exp/Cntr=0.3,0.1

Type RM Length L Ch R = 1 ,12395   ,300,300,300
XS GIS Cut Line= 3
     2082361.751      377614.397     2082155.278       378028.87
     2081964.295      378440.214
#Sta/Elev= 30
       0 2965.51    51.8  2941.1      62 2934.01    81.2 2933.27      95 2925.93
   149.7 2905.53   157.3 2900.74   179.3 2900.98   205.9 2887.18  248.41 2875.76
   270.9 2870.97   284.2 2865.84   296.6 2865.59   344.2 2853.82   369.9 2853.91
   377.2 2850.65   402.9 2846.92   413.9 2843.13   413.9 2843.12   428.5 2838.91
   464.8 2838.66   479.6 2842.75  494.37 2845.25   566.6 2853.06   660.5 2873.42
   765.4  2906.4   790.7 2917.61   819.7 2923.15   839.5 2932.99   916.6 2964.49
#Mann= 5 ,-1 , 0
       0      .1       0  248.41      .1       0   413.9    .045       0
   479.6      .1       0  494.37      .1       0
Bank Sta=413.9,479.6
XS Rating Curve= 0 ,0
Exp/Cntr=0.3,0.1

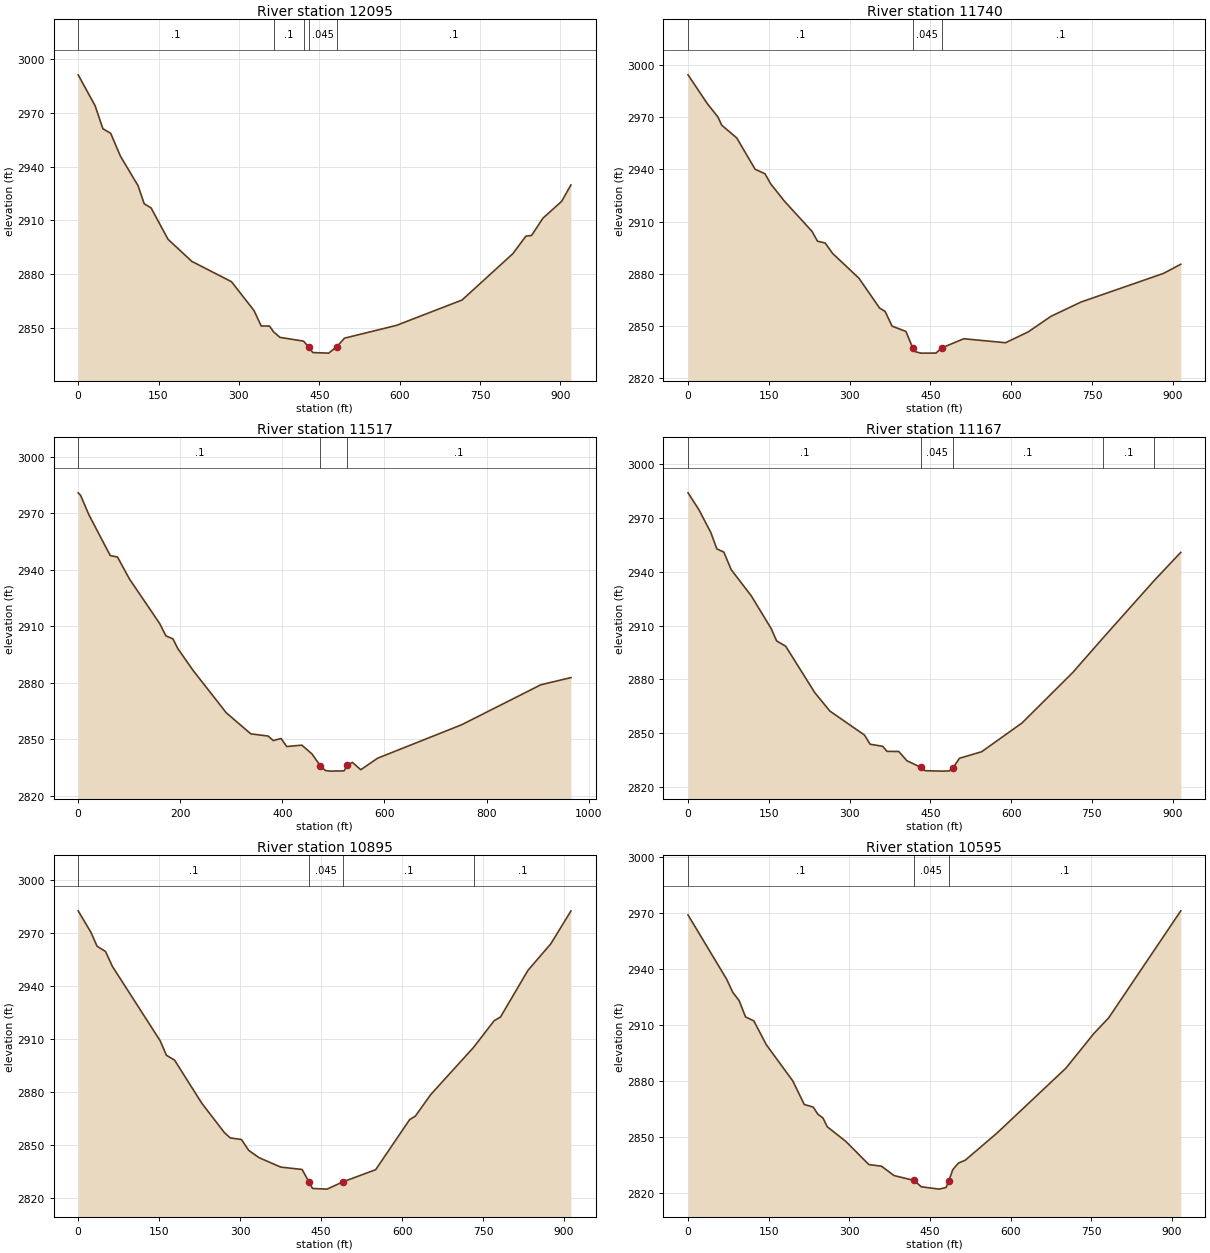
Type RM Length L Ch R = 1 ,12095   ,355,355,355
XS GIS Cut Line= 3
     2082110.649      377491.861     2081894.649      377904.139
     2081734.255       378329.16
#Sta/Elev= 30
       0 2991.23    31.6 2973.99    46.1  2961.2    60.7 2958.59    78.8 2945.89
   111.8 2929.37   123.2 2919.35   136.1 2916.99   167.7  2899.5   212.1 2887.18
   286.2 2875.83   328.1 2859.79   341.7 2851.13   357.2 2851.08  364.58  2847.9
   376.7 2844.79   420.6  2842.7   430.2 2839.41     438 2836.32   467.5    2836
   482.9 2839.63   497.2 2844.36   593.8 2851.45   716.5 2865.62   811.2 2891.43
   835.7 2901.27   846.3 2901.64   867.3 2911.22   902.4 2920.67   919.7 2929.81
#Mann= 5 ,-1 , 0
       0      .1       0  364.58      .1       0   420.6      .1       0
   430.2    .045       0   482.9      .1       0
Bank Sta=430.2,482.9
XS Rating Curve= 0 ,0
Exp/Cntr=0.3,0.1

Type RM Length L Ch R = 1 ,11740   ,222.2,222.2,222.2
XS GIS Cut Line= 2
     2081766.903      377296.145     2081455.214      378156.125
#Sta/Elev= 30
       0 2994.17    35.5 2977.78    55.6 2969.94    62.5 2965.29    90.5 2957.93
   124.6 2939.97   142.8 2937.43   153.3 2931.69   178.9  2921.7   230.2 2904.34
   240.4  2898.7   254.5 2897.71   268.4  2891.7   317.3 2877.47   355.6 2860.36
   365.9 2858.43   378.7    2850   404.5 2846.93   417.1  2837.5   422.3 2835.28
   432.3  2834.5   460.4 2834.53   470.8 2837.49   511.9 2842.75   589.5 2840.47
   631.3 2846.65   673.4 2855.56   729.1 2863.76   882.6 2880.24   914.7  2885.5
#Mann= 3 ,-1 , 0
       0      .1       0   417.1    .045       0   470.8      .1       0
Bank Sta=417.1,470.8
XS Rating Curve= 0 ,0
Exp/Cntr=0.3,0.1

Type RM Length L Ch R = 1 ,11517   ,350.9,350.9,350.9
XS GIS Cut Line= 3
2081677.19206783377258.1250461172081418.07504641377514.394627734
 2081358.2788107 378112.35698484
#Sta/Elev= 30
       0 2980.76     4.9 2979.35      21 2969.12    62.9 2947.45      77 2946.73
   100.3 2935.13   159.7 2911.41   171.9 2904.88   185.8 2903.26   195.1 2898.17
   225.3  2886.5   290.2 2864.05   338.3 2852.89   372.3 2851.72   382.2 2849.34
   397.5 2850.44   408.6 2846.18   438.3 2846.89   458.1 2842.24   474.6  2835.9
   484.4 2833.43   494.3 2833.12   520.7 2833.25   527.3 2836.11   537.2 2837.78
   553.7 2833.86   586.7 2839.98   751.2 2857.71   906.5 2878.93   965.4 2882.74
#Mann= 3 ,-1 , 0
       0      .1       0   474.6    .045       0   527.3      .1       0
Bank Sta=474.6,527.3
XS Rating Curve= 0 ,0
Exp/Cntr=0.3,0.1

Type RM Length L Ch R = 1 ,11167   ,271.9,271.9,271.9
XS GIS Cut Line= 2
2081607.43392162 377175.024081772080807.30333902377619.224689906
#Sta/Elev= 30
       0 2983.86      20 2974.57    42.5 2961.67    53.5 2952.66    66.5 2950.86
    80.1 2941.14   117.6 2926.46   154.4 2908.32   164.5 2901.48   181.4 2898.47
   235.5 2872.63   263.4 2862.41   327.7 2849.06   338.2 2843.95   361.5 2842.79
   369.6 2839.96   391.3 2839.92   406.5 2834.76   432.3 2831.11   440.3 2829.21
   470.9 2828.97   485.3 2829.06   492.3  2830.8   504.1 2836.12   545.4 2839.77
   620.4 2855.78   714.7  2883.9   770.8  2903.1   866.2 2935.17   915.2 2950.73
#Mann= 5 ,-1 , 0
       0      .1       0   432.3    .045       0   492.3      .1       0
   770.8      .1       0   866.2      .1       0
Bank Sta=432.3,492.3
XS Rating Curve= 0 ,0
Exp/Cntr=0.3,0.1

Type RM Length L Ch R = 1 ,10895   ,300,300,300
XS GIS Cut Line= 3
     2081462.308      376939.565     2081076.349      377181.628
     2080693.074      377430.973
#Sta/Elev= 30
       0 2982.52    23.6 2970.36      35 2962.47    50.7 2959.45    63.6 2950.93
   151.9 2908.91   163.5 2900.68   178.5 2897.97   228.9 2873.56   270.6 2856.98
   281.6 2853.89   302.5 2852.95   315.8 2846.84   334.9  2842.7   375.3 2837.33
   414.8 2835.99   427.7 2828.86   434.1 2825.24     461 2824.85   490.6 2828.99
   551.1 2835.87     614 2864.22   624.6  2866.2   653.1 2878.41  732.49 2905.17
   770.5 2920.24   782.3 2922.33   833.1 2948.75   875.7  2963.9   912.8 2982.43
#Mann= 4 ,-1 , 0
       0      .1       0   427.7    .045       0   490.6      .1       0
  732.49      .1       0
Bank Sta=427.7,490.6
XS Rating Curve= 0 ,0
Exp/Cntr=0.3,0.1

Type RM Length L Ch R = 1 ,10595   ,300,300,300
XS GIS Cut Line= 3
     2081292.821      376693.623     2080902.901      376942.433
      2080522.97      377190.638
#Sta/Elev= 30
       0 2969.03    71.8 2934.64    83.2 2927.62    95.1 2923.17   106.9 2914.49
   122.4 2912.33   145.7 2899.54   194.8 2880.23   216.2 2867.59   232.9  2866.2
   241.3 2862.43   250.8 2860.42     259 2855.68   293.6  2847.8   336.4 2835.43
   359.8 2834.57   383.1 2829.57   420.6 2826.93   433.7 2823.57   466.9  2822.3
   479.9 2823.16   484.6 2826.47   492.3 2832.68   502.9 2836.26   515.5 2837.76
   574.6  2852.3   702.7 2887.01   754.9 2905.63   782.3 2913.96   916.4 2971.24
#Mann= 3 ,-1 , 0
       0      .1       0   420.6    .045       0   484.6      .1       0
Bank Sta=420.6,484.6
XS Rating Curve= 0 ,0
Exp/Cntr=0.3,0.1

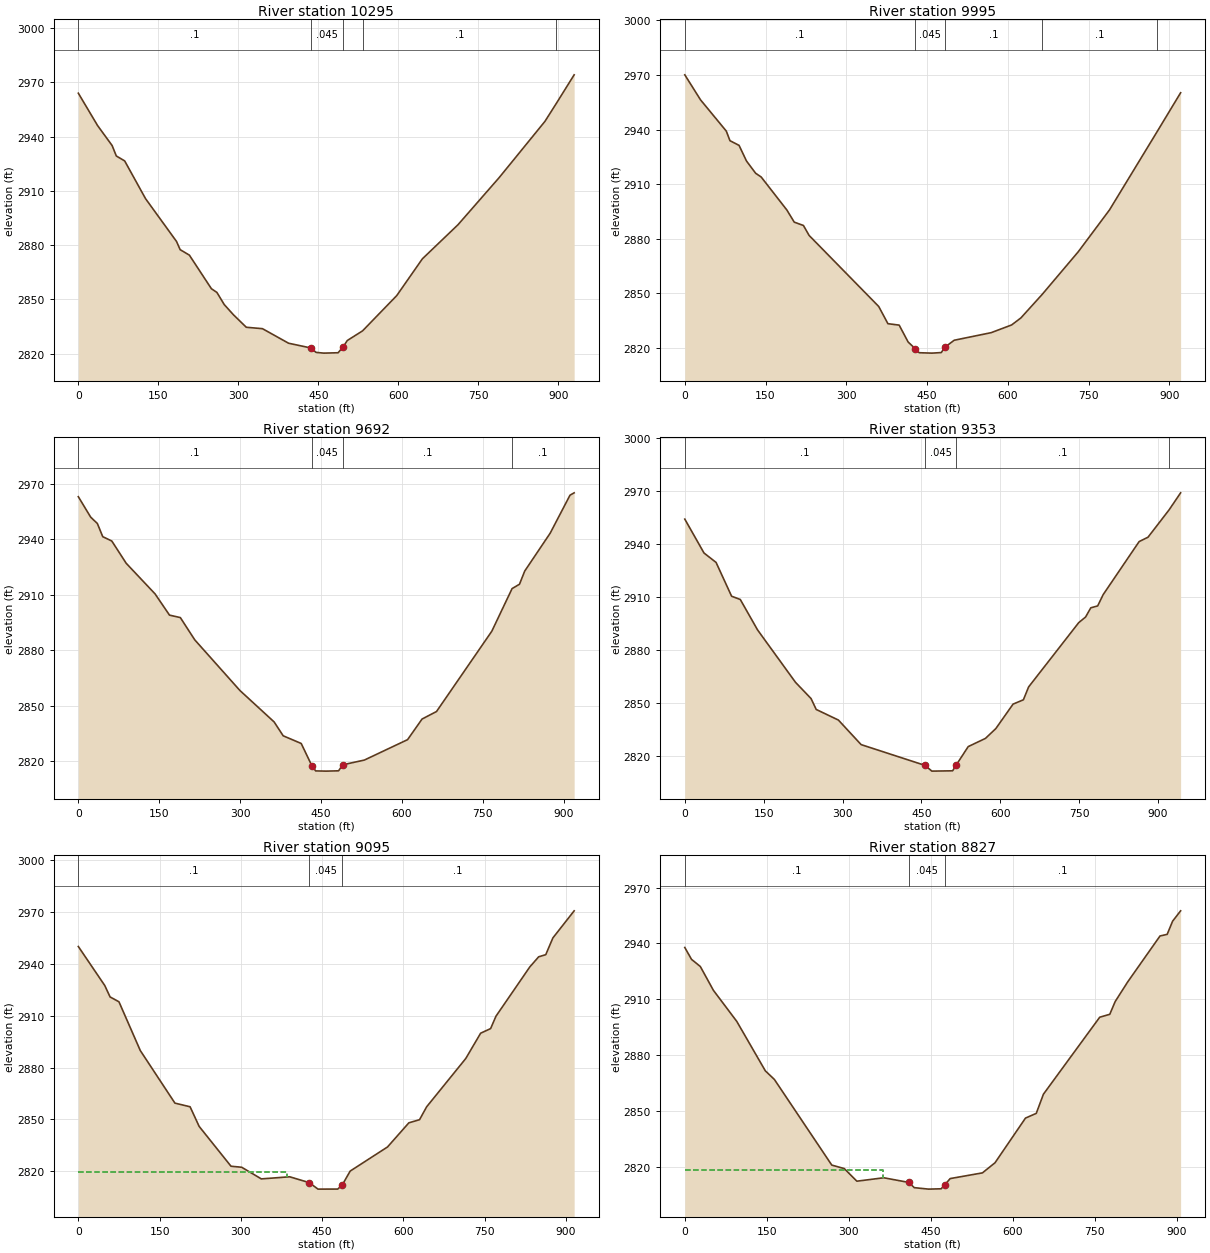
Type RM Length L Ch R = 1 ,10295   ,300,300,300
XS GIS Cut Line= 3
     2081220.624      376545.063     2080764.902      376690.727
     2080333.644      376823.399
#Sta/Elev= 30
       0 2964.03      36 2946.17    63.4 2935.07    71.2 2929.32    86.9 2926.59
     126 2905.73   184.1 2882.06   190.9 2877.52   208.2 2874.49   249.5 2855.93
   259.8 2853.88   273.6 2847.15   290.8 2841.53   314.9 2834.62   345.3 2833.83
   394.2 2825.79   435.5  2823.2   445.8 2820.73   460.1 2820.32   487.1 2820.53
   496.8  2823.9   504.3  2827.3  532.92 2832.63     597 2852.14     645 2872.44
   711.9 2891.33   789.2 2917.42   874.8 2948.43   896.4 2958.48   929.6 2974.18
#Mann= 5 ,-1 , 0
       0      .1       0   435.5    .045       0   496.8      .1       0
  532.92      .1       0   896.4      .1       0
Bank Sta=435.5,496.8
XS Rating Curve= 0 ,0
Exp/Cntr=0.3,0.1

Type RM Length L Ch R = 1 ,9995    ,302.7,302.7,302.7
XS GIS Cut Line= 3
     2081162.063      376297.197     2080721.495      376422.838
     2080279.916       376561.75
#Sta/Elev= 30
       0 2970.06    29.3 2956.28    77.1 2939.12    83.9 2933.85   100.8 2931.28
   114.6 2922.68   131.6 2915.95   141.9 2913.88   189.6 2895.74   203.3 2889.07
   220.4 2887.23   230.9 2881.77   360.2 2842.71   377.3 2833.24   398.2 2832.46
   414.8 2823.19   428.5 2819.36   435.3 2817.28   459.2 2817.06   476.4 2817.37
   483.2 2820.34   500.4 2824.14   569.1 2828.31   607.1 2832.55   624.3 2836.41
  664.08 2849.42   730.9  2872.8   788.9  2895.8  876.53 2938.42     921  2960.2
#Mann= 5 ,-1 , 0
       0      .1       0   428.5    .045       0   483.2      .1       0
  664.08      .1       0  876.53      .1       0
Bank Sta=428.5,483.2
XS Rating Curve= 0 ,0
Exp/Cntr=0.3,0.1

Type RM Length L Ch R = 1 ,9692    ,339.4,339.4,339.4
XS GIS Cut Line= 2
2081093.03161877376063.3273397872080191.34235011376244.368265072
#Sta/Elev= 30
       0  2963.1    22.9 2952.04    35.3 2948.59    45.3 2941.46    62.1  2939.1
    88.8 2927.05   142.4 2910.45   169.1 2898.98   189.2 2897.65     216 2885.58
   299.7 2858.17   363.2 2841.13     380 2833.63   413.4 2829.48   433.5 2817.23
   440.2 2814.62     460  2814.5   482.8 2814.67   490.4 2817.93   530.5 2820.48
   610.7 2831.54   637.6 2842.71   664.4 2846.78     767 2890.28  804.56 2913.34
   818.3  2915.7     828 2922.83   875.2 2943.33     912 2963.92   919.7  2965.2
#Mann= 4 ,-1 , 0
       0      .1       0   433.5    .045       0   490.4      .1       0
  804.56      .1       0
Bank Sta=433.5,490.4
XS Rating Curve= 0 ,0
Exp/Cntr=0.3,0.1

Type RM Length L Ch R = 1 ,9353    ,257.9,257.9,257.9
XS GIS Cut Line= 2
2081022.72446332375843.6174790052080080.60858028375880.528735616
#Sta/Elev= 30
       0 2954.21    36.5 2935.05    59.5  2929.7      89 2910.59   105.5 2908.75
   138.3 2891.55   210.5 2861.88   240.1 2852.68   249.9 2846.52   292.1 2840.52
   335.3 2826.63  456.74 2814.88   469.8 2811.63   509.3 2811.81   515.9    2815
   538.9  2825.5   571.7 2830.15   591.4 2835.69   624.2 2849.55   643.8 2851.98
   653.8 2859.27     749 2895.63   762.1 2898.83     772 2904.03   785.1 2905.11
   795.5 2911.49   863.9  2941.5   880.8 2943.98  920.97 2959.49   942.8 2969.09
#Mann= 4 ,-1 , 0
       0      .1       0  456.74    .045       0   515.9      .1       0
  920.97     .06       0
Bank Sta=456.74,515.9
XS Rating Curve= 0 ,0
Exp/Cntr=0.3,0.1

Type RM Length L Ch R = 1 ,9095    ,267.6,267.6,267.6
XS GIS Cut Line= 3
     2080989.068      375623.631     2080529.807      375608.676
     2080074.323      375596.185
#Sta/Elev= 30
       0 2950.04    48.8 2927.46    58.6 2920.86      75 2918.06   114.4 2889.83
   178.3 2859.42   206.3 2857.31     223 2845.96   281.8 2822.91   301.5 2822.32
   337.8 2815.58   390.2  2816.8   426.3 2813.41   442.4 2809.66   478.8 2809.69
     487    2812   501.8 2820.11   570.7 2834.05   610.1 2848.02   629.8 2849.83
   642.9 2857.28   715.1 2885.22   742.6 2899.88     761 2902.54   770.9 2909.72
   833.3  2938.2   849.7 2944.07   862.8 2945.31   875.9 2954.99   915.2 2970.68
#Mann= 3 ,-1 , 0
       0      .1       0   426.3    .045       0     487      .1       0
#XS Ineff= 2 , 0
          385.86 2819.63
Permanent Ineff=
       F       F
Bank Sta=426.3,487
XS Rating Curve= 0 ,0
Exp/Cntr=0.3,0.1

Type RM Length L Ch R = 1 ,8827    ,273.5,273.5,273.5
XS GIS Cut Line= 2
2080989.32856448375353.2250697382080082.36625916375335.648280875
#Sta/Elev= 30
       0 2937.81    12.3 2931.44    28.4 2927.61    52.3 2914.84      95 2898.19
   147.4 2871.58   163.9 2866.99   268.9 2821.02   291.8 2819.14   314.8 2812.38
     364 2814.22     410  2811.7   419.8 2808.91   446.1 2808.12     469  2808.3
   475.4 2810.38   485.5 2813.78   544.5 2816.84   567.5 2822.26   623.3 2846.25
     643 2848.78   656.1 2859.07   759.1 2900.39   777.5 2901.95   787.3 2908.76
   810.3 2919.35   869.4 2943.99   882.5 2944.86   892.4 2951.92   907.1 2957.49
#Mann= 3 ,-1 , 0
       0      .1       0     410    .045       0   475.4      .1       0
#XS Ineff= 2 , 0
          362.74  2818.2
Permanent Ineff=
       F       F
Bank Sta=410,475.4
XS Rating Curve= 0 ,0
Exp/Cntr=0.3,0.1

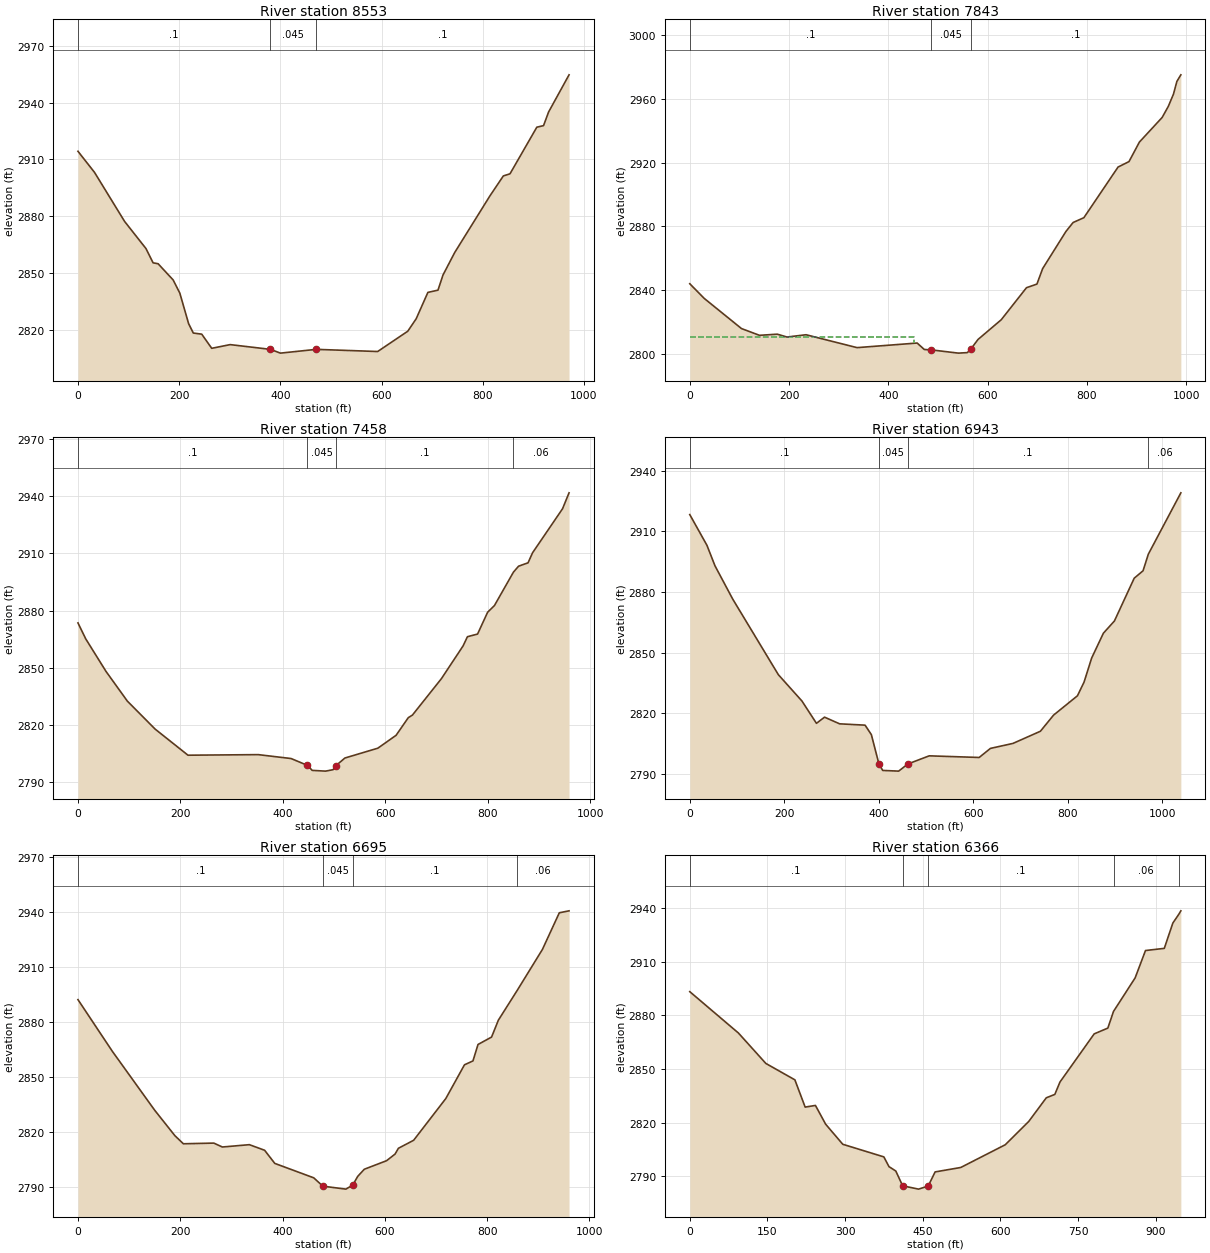
Type RM Length L Ch R = 1 ,8553    ,710.6,710.6,710.6
XS GIS Cut Line= 2
2081008.66303223375021.0237602342080047.21268144 375154.60735559
#Sta/Elev= 30
       0 2914.26    32.6 2903.18    92.2 2877.23   134.4 2862.93   148.5 2855.38
   158.4 2854.91   188.2 2846.33   201.3 2839.42   218.7  2823.3     228 2818.32
   244.6 2817.74   264.4 2810.26   300.9 2812.21   380.4 2809.71   400.2 2807.72
   471.1 2809.71   592.4 2808.57   651.9 2819.28   668.5 2825.84   691.7 2839.79
   711.6 2840.95   721.5 2848.93   744.7 2860.84   814.3 2890.73   840.8 2901.25
     854 2902.39     907 2926.98   920.3 2927.82   930.2 2934.97   970.7 2954.63
#Mann= 3 ,-1 , 0
       0      .1       0   380.4    .045       0   471.1      .1       0
Bank Sta=380.4,471.1
XS Rating Curve= 0 ,0
Exp/Cntr=0.3,0.1

Type RM Length L Ch R = 1 ,7843    ,385,385,385
XS GIS Cut Line= 2
2080441.43205757374235.3733767322080027.87174931375134.218474749
#Sta/Elev= 30
       0 2843.85    29.1 2834.64   104.2 2815.68   140.4 2811.44   176.4 2812.16
   195.8 2810.36   234.2  2811.8     337  2803.7   458.1 2806.59   472.5 2802.54
   486.7 2802.29   541.1 2800.25   559.2 2800.57   565.9 2802.64   580.7 2808.83
   627.5 2821.22   678.4 2841.37   699.4 2843.63   710.9 2853.34   757.8 2876.67
   772.3 2882.33     794 2885.35   862.9 2917.19   884.9  2920.6   905.9 2932.88
   951.7 2948.34   964.1 2955.29   974.5 2962.99   981.4 2971.01   989.4 2975.13
#Mann= 3 ,-1 , 0
       0      .1       0   486.7    .045       0   565.9      .1       0
#XS Ineff= 2 , 0
          451.42 2810.69
Permanent Ineff=
       F       F
Bank Sta=486.7,565.9
XS Rating Curve= 0 ,0
Exp/Cntr=0.3,0.1

Type RM Length L Ch R = 1 ,7458    ,514.7,514.7,514.7
XS GIS Cut Line= 2
2080339.61838328374098.2282835152079652.36593875374766.146260295
#Sta/Elev= 30
       0  2873.5    15.2  2865.1    54.8 2847.98    96.4 2832.39   150.5  2817.7
   214.7 2803.96   351.8 2804.26   415.9 2802.21   447.9 2798.61   457.1 2795.98
   483.2 2795.59   497.8 2796.34   502.8 2798.33   520.9 2802.48   585.2 2807.65
   620.8 2814.42   644.6 2823.69   652.7 2825.06   709.2 2844.19   751.5  2861.4
     760 2866.25   779.8 2867.65   799.4 2879.11   812.7 2882.63  849.77 2900.19
   859.8 2903.32   878.3  2905.1   887.1 2910.38   945.6 2933.51   958.3 2941.89
#Mann= 4 ,-1 , 0
       0      .1       0   447.9    .045       0   502.8      .1       0
  849.77     .06       0
Bank Sta=447.9,502.8
XS Rating Curve= 0 ,0
Exp/Cntr=0.3,0.1

Type RM Length L Ch R = 1 ,6943    ,248.5,248.5,248.5
XS GIS Cut Line= 3
 2079543.3898478373753.7232218082079745.52291972374472.613886289
2079631.27379212374741.538755887
#Sta/Elev= 30
       0 2918.32    36.3 2903.13    53.3 2892.98    90.8 2876.51   187.4 2839.06
   237.4    2826     268 2814.97   285.1 2818.03     317 2814.73   370.9 2814.07
   384.2 2809.37   400.2 2794.86   408.2 2791.65   441.9 2791.31   461.4 2794.85
   506.6 2798.88   612.3 2798.07   636.1 2802.56   683.8 2805.03   741.8 2811.05
   769.7 2819.04   820.2 2828.61   834.2 2835.39   850.3 2847.32   875.1  2859.6
   898.4 2865.64   940.3 2886.82     959  2890.5  970.13  2898.7    1039  2929.1
#Mann= 4 ,-1 , 0
       0      .1       0   400.2    .045       0   461.4      .1       0
  970.13     .06       0
Bank Sta=400.2,461.4
XS Rating Curve= 0 ,0
Exp/Cntr=0.3,0.1

Type RM Length L Ch R = 1 ,6695    ,328.2,328.2,328.2
XS GIS Cut Line= 3
     2079389.812      373800.854     2079456.961      374306.114
     2079519.455      374752.349
#Sta/Elev= 30
       0  2892.2    67.1 2864.07   149.9 2831.94   189.6    2818   206.1  2813.6
   265.7 2813.97   282.3 2811.84   335.2 2813.11     365 2810.06   384.9  2802.9
     461 2795.04   478.8 2790.49   523.9 2788.87   537.3 2791.07   547.1 2795.84
     560 2799.72   603.4 2804.36     620 2807.96   626.6 2811.14   656.4 2815.51
   719.3 2838.26   755.8 2856.66   772.4 2858.78   782.3 2867.75   808.8 2871.79
     822 2880.96  859.11 2897.32   908.2 2919.56   941.3 2939.57   960.3 2940.63
#Mann= 4 ,-1 , 0
       0      .1       0   478.8    .045       0   537.3      .1       0
  859.11     .06       0
Bank Sta=478.8,537.3
XS Rating Curve= 0 ,0
Exp/Cntr=0.3,0.1

Type RM Length L Ch R = 1 ,6366    ,255.4,255.4,255.4
XS GIS Cut Line= 2
2079105.72780512373787.1191206472079214.70389607374729.235003683
#Sta/Elev= 30
       0 2893.28      94 2870.12   146.9 2853.11     203 2843.93   222.8 2828.68
   242.7 2829.61   262.4  2819.1   295.5 2807.87   374.8 2800.81   384.7 2795.36
   397.9 2792.89   411.1 2784.63   441.8 2782.77   460.4 2784.48   473.8  2792.4
   523.4 2794.89   609.3 2807.61   654.7 2820.67   688.5 2833.88     705 2835.78
   714.9 2842.69     781 2869.65   807.4  2872.9  818.33 2882.22   860.1 2900.99
   880.1  2916.3   916.4 2917.51   932.9 2931.66  944.65 2936.68   948.4 2938.52
#Mann= 5 ,-1 , 0
       0      .1       0   411.1    .045       0   460.4      .1       0
  818.33     .06       0  944.65      .1       0
Bank Sta=411.1,460.4
XS Rating Curve= 0 ,0
Exp/Cntr=0.3,0.1

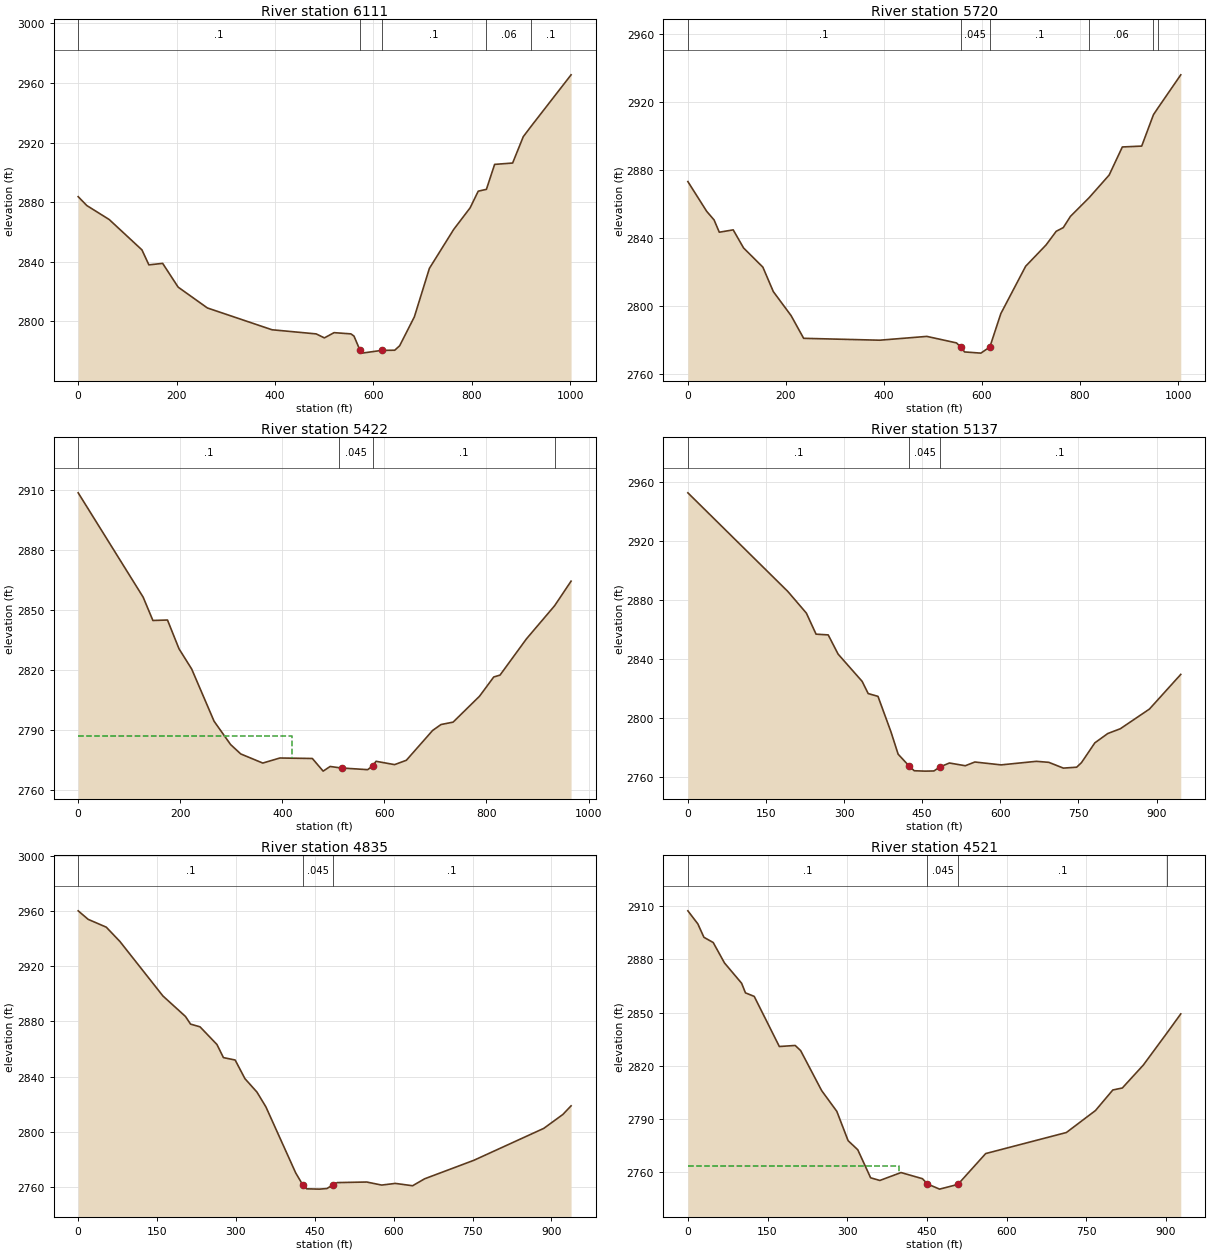
Type RM Length L Ch R = 1 ,6111    ,390.5,390.5,390.5
XS GIS Cut Line= 3
 2079031.9052919373785.361441761 2078906.1070808374123.055196399
2079012.57082415374755.600186977
#Sta/Elev= 30
       0 2883.72    17.5 2877.78      63  2868.4   129.6 2848.01   143.7 2837.96
   171.7 2838.96   203.1 2823.04   262.6 2809.04   393.9 2794.41   483.7 2791.64
   500.4 2788.95   520.1 2792.47   554.3 2791.65   560.6 2790.14   572.6  2780.8
   576.9 2778.73   616.8 2780.57   643.4 2780.68   653.4 2783.69   683.3 2803.09
   713.8 2835.59   763.2 2861.73   796.5 2876.18   813.1 2887.41  829.71 2888.64
   846.4 2905.38     883  2906.3   904.6 2923.97  921.02 2931.14  1001.8 2965.49
#Mann= 5 ,-1 , 0
       0      .1       0   572.6    .045       0   616.8      .1       0
  829.71     .06       0  921.02      .1       0
Bank Sta=572.6,616.8
XS Rating Curve= 0 ,0
Exp/Cntr=0.3,0.1

Type RM Length L Ch R = 1 ,5720    ,298.6,298.6,298.6
XS GIS Cut Line= 3
2078933.47527427373785.3614417612078856.13740327373969.917724818
2078362.22963624374606.197481645
#Sta/Elev= 30
       0 2872.97    38.4 2855.47    53.4 2850.45    64.1  2843.2    92.5 2844.58
   113.6 2833.96     153 2822.66   174.3 2808.29   210.6 2794.15   236.2 2780.81
   391.3  2779.7   487.6 2781.94     548 2778.11   556.3 2775.77   564.6  2772.8
   597.8  2772.1   616.1 2775.71   638.5 2795.34   689.2 2823.21   730.7 2835.69
   751.5 2843.74   765.9 2845.91   780.5 2852.51  818.53 2863.47   859.5 2876.82
   886.4 2893.33   925.9 2893.84  949.84 2912.29  958.46    2916  1005.6 2935.75
#Mann= 6 ,-1 , 0
       0      .1       0   556.3    .045       0   616.1      .1       0
  818.53     .06       0  949.84      .1       0  958.46    .055       0
Bank Sta=556.3,616.1
XS Rating Curve= 0 ,0
Exp/Cntr=0.3,0.1

Type RM Length L Ch R = 1 ,5422    ,284.8,284.8,284.8
XS GIS Cut Line= 3
2078845.59132996373674.6276719262078685.64255131 373889.06449605
2078112.63923439374288.057603232
#Sta/Elev= 30
       0 2908.72   127.3 2856.57   146.4 2844.91     175 2845.14   197.6 2830.74
   222.4 2820.64   266.3 2794.54   298.6 2782.91   318.6 2778.19   361.7 2773.64
   395.2 2776.17   458.8 2775.93     480 2769.61   493.7 2771.94   510.7 2771.34
   516.7 2771.17   567.2 2770.34   576.7 2772.16   583.7 2774.52     620 2772.86
     643 2775.03   694.5 2789.94     711 2792.91   734.6  2794.1   786.4 2807.05
   814.3 2816.68   826.5 2817.59   878.4 2835.74  933.53 2852.28   965.8 2864.57
#Mann= 4 ,-1 , 0
       0      .1       0   510.7    .045       0   576.7      .1       0
  933.53     .06       0
#XS Ineff= 2 , 0
          418.31 2787.28
Permanent Ineff=
       F       F
Bank Sta=516.7,576.7
XS Rating Curve= 0 ,0
Exp/Cntr=0.3,0.1

Type RM Length L Ch R = 1 ,5137    ,302,302,302
XS GIS Cut Line= 2
2078732.07999349 373497.232302852078009.67397123374108.904555269
#Sta/Elev= 30
       0 2952.72   192.1 2885.66   227.6    2871   246.2  2856.7   269.5 2856.21
   288.5 2843.17   334.7 2824.63   346.3 2816.35   365.1 2814.46   390.1 2790.28
   403.8 2775.17   425.6 2766.87   434.7 2763.92   455.4 2763.66   472.6 2763.77
   483.6 2766.43   502.3 2769.18   532.8 2767.32   551.1 2769.86   601.5  2767.9
   669.3 2770.32   693.1 2769.64   721.1 2765.71   746.7 2766.33     756 2769.47
   781.6 2782.88   806.4  2789.2   830.5 2792.45   886.4 2805.81   946.6 2829.37
#Mann= 3 ,-1 , 0
       0      .1       0   425.6    .045       0   483.6      .1       0
Bank Sta=425.6,483.6
XS Rating Curve= 0 ,0
Exp/Cntr=0.3,0.1

Type RM Length L Ch R = 1 ,4835    ,314.2,314.2,314.2
XS GIS Cut Line= 2
2078377.02885846373200.184571072 2077937.6091369374028.051326501
#Sta/Elev= 30
       0  2960.2    18.9 2954.03    53.4 2948.35    79.4 2937.95   161.1 2898.44
     204 2883.57   213.7 2878.01   231.7 2876.03   263.9 2863.22   276.2 2853.72
   298.5 2851.96   317.1 2838.44   339.9 2828.72   356.9 2818.02   413.7 2770.01
   427.2 2761.28   434.5  2758.5   458.8 2758.29   473.1 2758.72   484.2 2761.35
   492.8 2763.03   548.6 2763.45   577.1 2761.23   603.1 2762.44   635.9 2760.74
   658.8 2765.78   752.4  2779.2   885.4 2802.37   921.7 2812.47   937.3 2818.72
#Mann= 3 ,-1 , 0
       0      .1       0   427.2    .045       0   484.2      .1       0
Bank Sta=427.2,484.2
XS Rating Curve= 0 ,0
Exp/Cntr=0.3,0.1

Type RM Length L Ch R = 1 ,4521    ,226.1,226.1,226.1
XS GIS Cut Line= 2
2078062.71192186373098.9020300472077689.69340267373948.446825074
#Sta/Elev= 30
       0 2907.51    18.8 2900.12    30.2 2892.55    47.7 2889.58    68.9 2878.05
   101.2 2866.54   108.4 2861.12   124.9 2859.12   172.2 2830.77     202 2831.37
   212.3 2828.45   251.8 2805.85   280.4 2794.09   301.6 2777.53   319.8 2772.39
     344 2756.53   361.4 2755.02   401.2 2759.49   441.6 2756.02     451 2753.04
   473.8 2750.12   508.3 2752.79   560.6 2770.23   712.5 2782.14   767.3 2794.58
   799.9 2806.19   817.8 2807.32   857.2 2820.24  901.39 2838.26   927.8 2849.21
#Mann= 4 ,-1 , 0
       0      .1       0     451    .045       0   508.3      .1       0
  901.39     .06       0
#XS Ineff= 2 , 0
          397.23 2762.94
Permanent Ineff=
       F       F
Bank Sta=451,508.3
XS Rating Curve= 0 ,0
Exp/Cntr=0.3,0.1