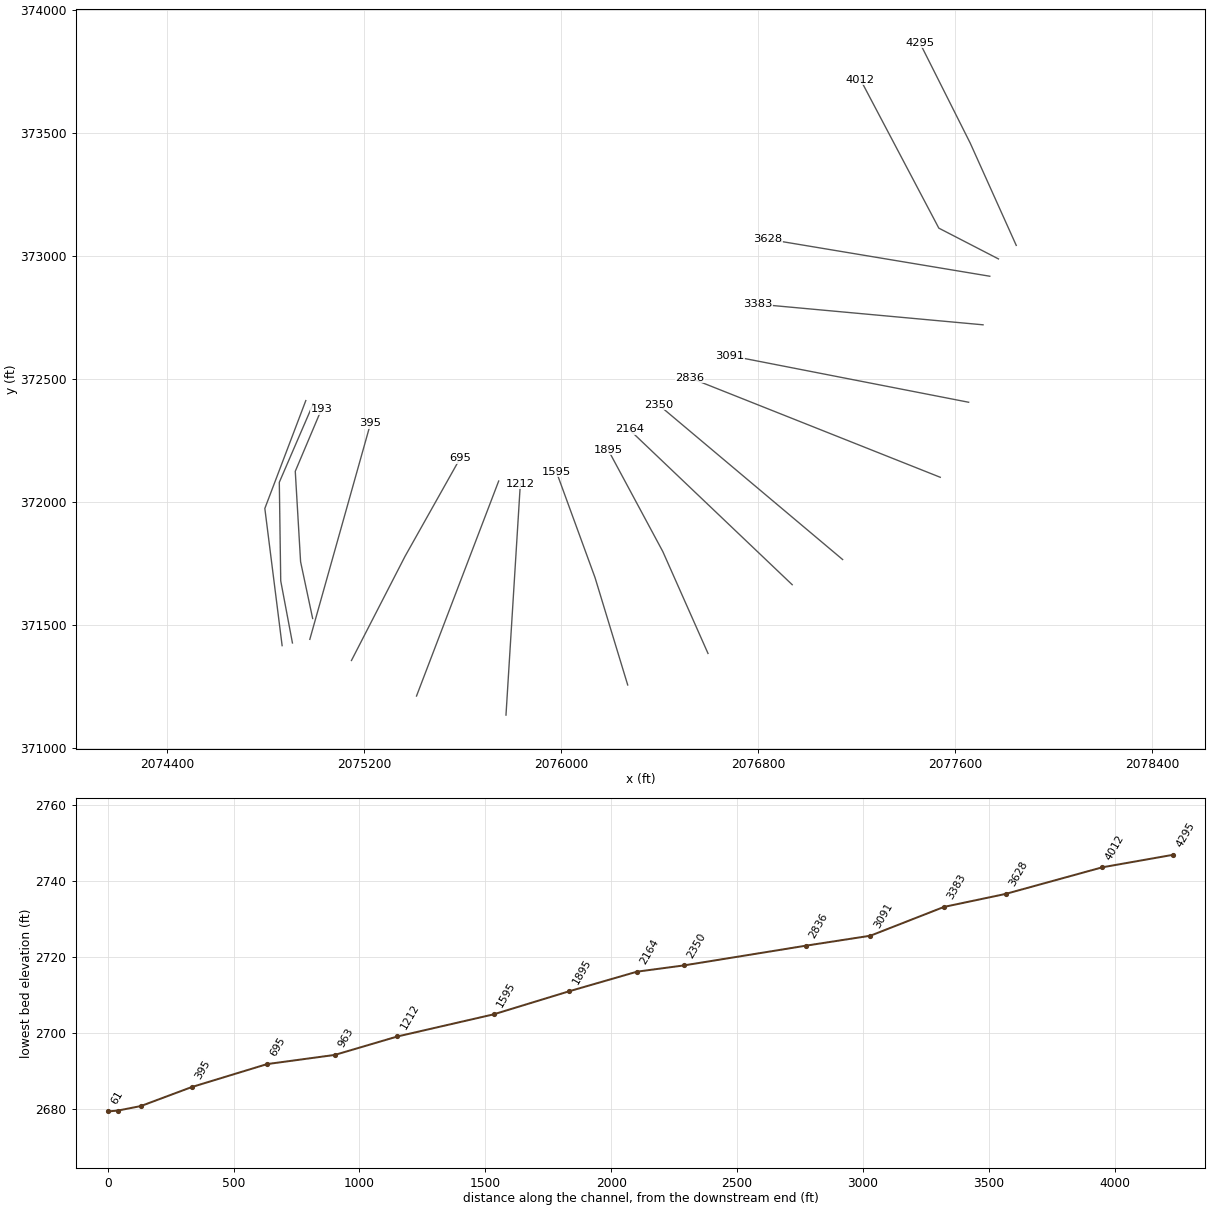
HEC-RAS study SFBIGCLRCK.prj: SFBIGCLRCK

--- SFBIGCLRCK.g01 (geometry) --- (continued)

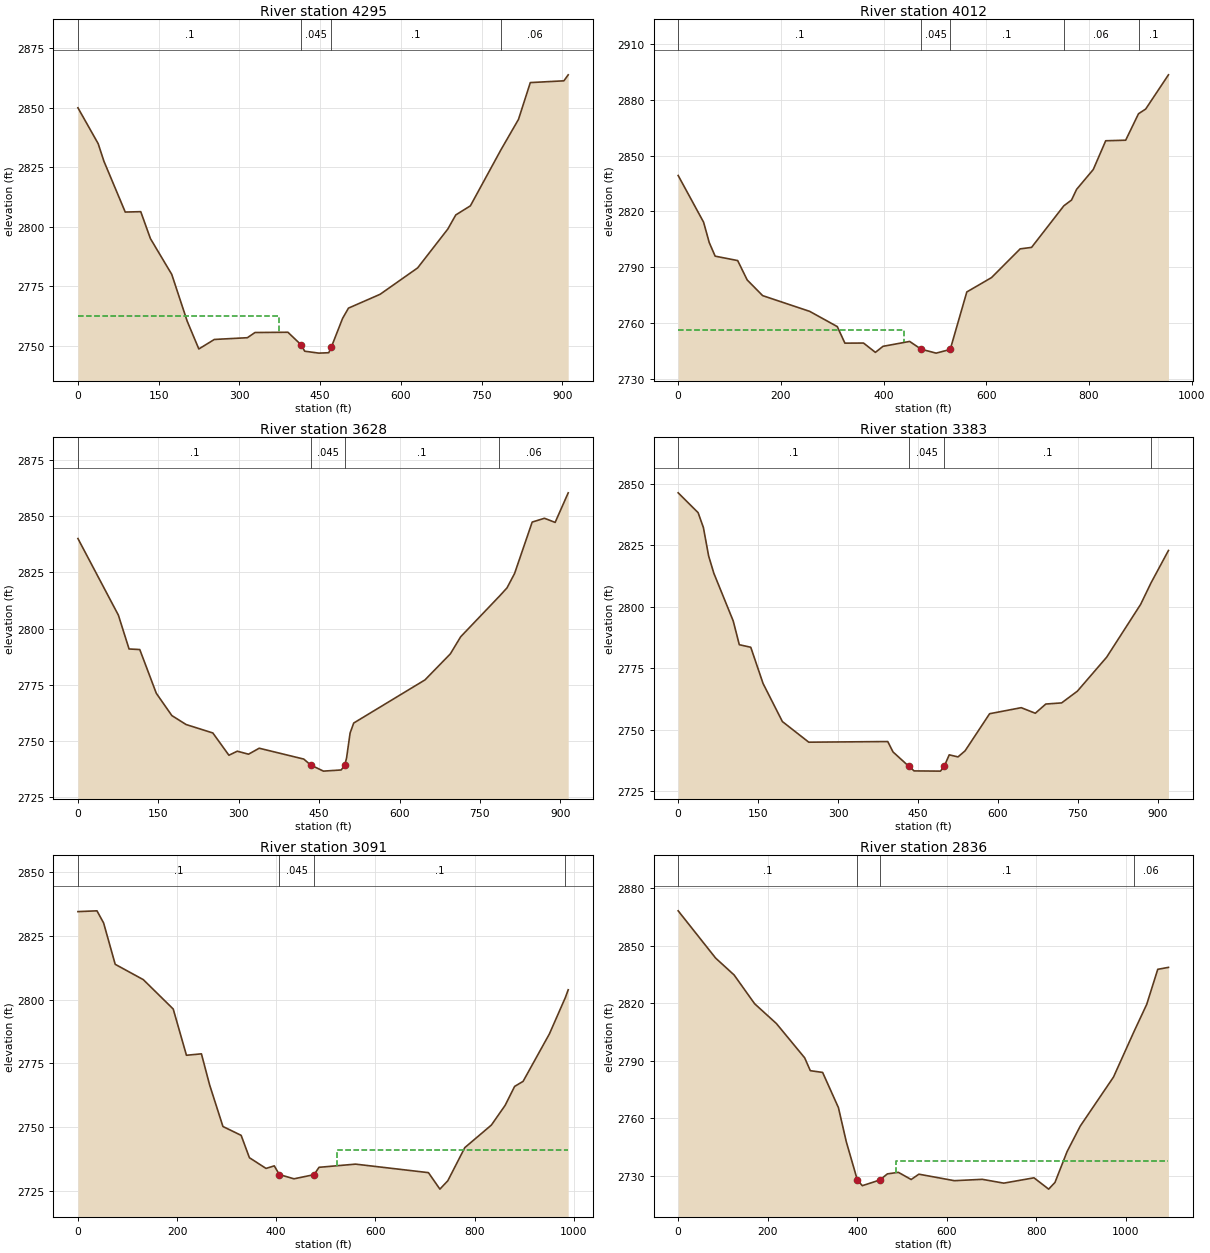
Type RM Length L Ch R = 1 ,4295    ,282.5,282.5,282.5
XS GIS Cut Line= 3
     2077847.868      373042.485     2077660.816      373458.142
     2077456.493      373864.652
#Sta/Elev= 30
       0 2850.07    37.6 2835.01    48.3 2827.62    87.9 2806.27   116.7 2806.43
   134.7 2795.11   174.3 2780.08     203 2760.41   224.6 2748.75   253.4 2752.74
   314.8 2753.48     329 2755.66   390.1 2755.77     414 2750.62   421.4  2747.8
   447.7    2747   465.9 2747.17   470.8 2749.56   491.6 2761.57   502.6 2765.91
   561.3 2771.71   631.1 2782.81   687.2 2799.15   701.9 2805.05   729.1 2808.89
   785.5 2832.29   818.4 2845.19   840.4 2860.66   902.8  2861.4   910.8 2863.92
#Mann= 4 ,-1 , 0
       0      .1       0     414    .045       0   470.8      .1       0
   785.5     .06       0
#XS Ineff= 2 , 0
          373.43  2762.8
Permanent Ineff=
       F       F
Bank Sta=414,470.8
XS Rating Curve= 0 ,0
Exp/Cntr=0.3,0.1

Type RM Length L Ch R = 1 ,4012    ,384.5,384.5,384.5
XS GIS Cut Line= 3
2077775.62437044372987.5823672512077533.45527944373112.572865829
2077215.12010338373716.042616779
#Sta/Elev= 30
       0 2839.27    49.5 2814.15    60.5 2803.21      72 2795.87   115.9 2793.49
   134.4 2783.06   164.5 2774.63   256.2 2766.15   309.9 2757.96   324.7 2749.06
     361 2749.11   384.1  2744.1   398.9 2747.35   450.8 2749.98   473.3 2745.78
   502.4 2743.69   529.8 2745.67   562.1  2776.6   610.3 2784.35     666 2799.79
   688.2 2800.58   751.1 2822.97   766.1 2826.08   775.9  2831.8   808.4  2842.5
   832.6 2857.96   871.5 2858.26   896.5 2872.51   910.4 2875.01   954.8 2893.44
#Mann= 5 ,-1 , 0
       0      .1       0   473.3    .045       0   529.8      .1       0
   751.1     .06       0   896.5      .1       0
#XS Ineff= 2 , 0
          439.85 2755.97
Permanent Ineff=
       F       F
Bank Sta=473.3,529.8
XS Rating Curve= 0 ,0
Exp/Cntr=0.3,0.1

Type RM Length L Ch R = 1 ,3628    ,244.4,244.4,244.4
XS GIS Cut Line= 2
2077740.47079271  372917.2752118 2076838.1956311373067.654405402
#Sta/Elev= 30
       0 2840.05    75.5 2805.99    95.4 2790.96   115.4 2790.71   146.2 2771.28
   175.2 2761.37   201.8 2757.38   251.7 2753.63   281.7 2743.73   297.3 2745.53
   318.3  2744.2   338.2 2746.85   421.4 2742.02   434.2  2739.4     458 2736.67
   491.2 2737.19   497.9 2739.34   501.2 2742.54   507.8 2753.63   514.5 2758.04
   647.5 2777.22   694.8 2788.79   714.1  2796.4  786.15 2814.38   800.5 2818.12
   814.6 2824.49   847.5 2847.37   870.4 2849.06   890.3 2847.22   914.7 2860.37
#Mann= 4 ,-1 , 0
       0      .1       0   434.2    .045       0   497.9      .1       0
  786.15     .06       0
Bank Sta=434.2,497.9
XS Rating Curve= 0 ,0
Exp/Cntr=0.3,0.1

Type RM Length L Ch R = 1 ,3383    ,292.5,292.5,292.5
XS GIS Cut Line= 2
2077713.12912115372720.0245812312076797.18312375372804.002572463
#Sta/Elev= 30
       0 2846.24    37.4 2838.19    47.3 2832.17    57.2 2820.57      67 2813.54
   103.3 2794.21   114.7 2784.57   136.2 2783.54   159.3 2768.81   195.5 2753.38
     245    2745   393.2 2745.26   403.1 2741.03   432.7 2735.21   442.6 2733.34
   492.1 2733.25   499.2 2735.23   508.5 2739.87     525 2739.02   538.2 2741.47
   584.3 2756.56   643.6 2759.01     670 2756.75   689.7 2760.49   719.4 2760.95
     749 2765.73   803.9 2779.52   867.6 2800.95  886.93 2809.61   919.8 2822.83
#Mann= 4 ,-1 , 0
       0      .1       0   432.7    .045       0   499.2      .1       0
  886.93     .06       0
Bank Sta=432.7,499.2
XS Rating Curve= 0 ,0
Exp/Cntr=0.3,0.1

Type RM Length L Ch R = 1 ,3091    ,254.7,254.7,254.7
XS GIS Cut Line= 2
2077654.53982494372405.5953582442076683.91048442372595.034082652
#Sta/Elev= 30
       0 2834.58    38.4 2834.89    51.8 2830.13    75.2  2813.9     132 2807.86
   192.2 2796.35   218.9  2778.2   249.1 2778.76   265.7 2766.51   292.5 2750.24
   329.2 2746.77   345.9 2737.99   379.4 2733.79   396.1 2734.79   406.1  2731.4
   435.8 2729.71   476.3 2731.35   486.3 2734.22   559.9 2735.47     707 2732.13
   730.1 2725.66   746.1 2728.96   780.3 2741.94     834 2750.82   861.6 2758.52
   880.8 2765.97   897.9 2767.96     951  2786.6  983.11 2800.84   988.9  2803.9
#Mann= 4 ,-1 , 0
       0      .1       0   406.1    .045       0   476.3      .1       0
  983.11     .06       0
#XS Ineff= 2 , 0
                          521.77         2741.02
Permanent Ineff=
       F       F
Bank Sta=406.1,476.3
XS Rating Curve= 0 ,0
Exp/Cntr=0.3,0.1

Type RM Length L Ch R = 1 ,2836    ,485.6,485.6,485.6
XS GIS Cut Line= 2
2077539.31420906372100.9310179582076521.81343157372505.197161799
#Sta/Elev= 30
       0 2868.18    83.7 2843.52   124.9 2834.74   170.8 2819.71   219.3 2809.42
   282.5 2791.52   295.1 2784.82   322.6 2783.91   357.9 2765.54   375.5 2747.71
   400.2 2727.77   411.3 2724.85   449.7 2727.75   467.3    2731   491.7 2731.81
   520.3 2728.07   537.6 2730.84   616.9 2727.45   679.1 2728.16   727.1 2726.17
   794.6 2728.95   827.4 2723.05   841.5 2726.55   868.6 2742.67     898 2755.95
   972.2 2781.51 1017.57 2805.03  1046.3 2819.37    1071 2837.68  1094.9 2838.69
#Mann= 4 ,-1 , 0
       0      .1       0   400.2    .045       0   449.7      .1       0
 1017.57     .06       0
#XS Ineff= 2 , 0
                           486.2         2737.65
Permanent Ineff=
       F       F
Bank Sta=400.2,449.7
XS Rating Curve= 0 ,0
Exp/Cntr=0.3,0.1

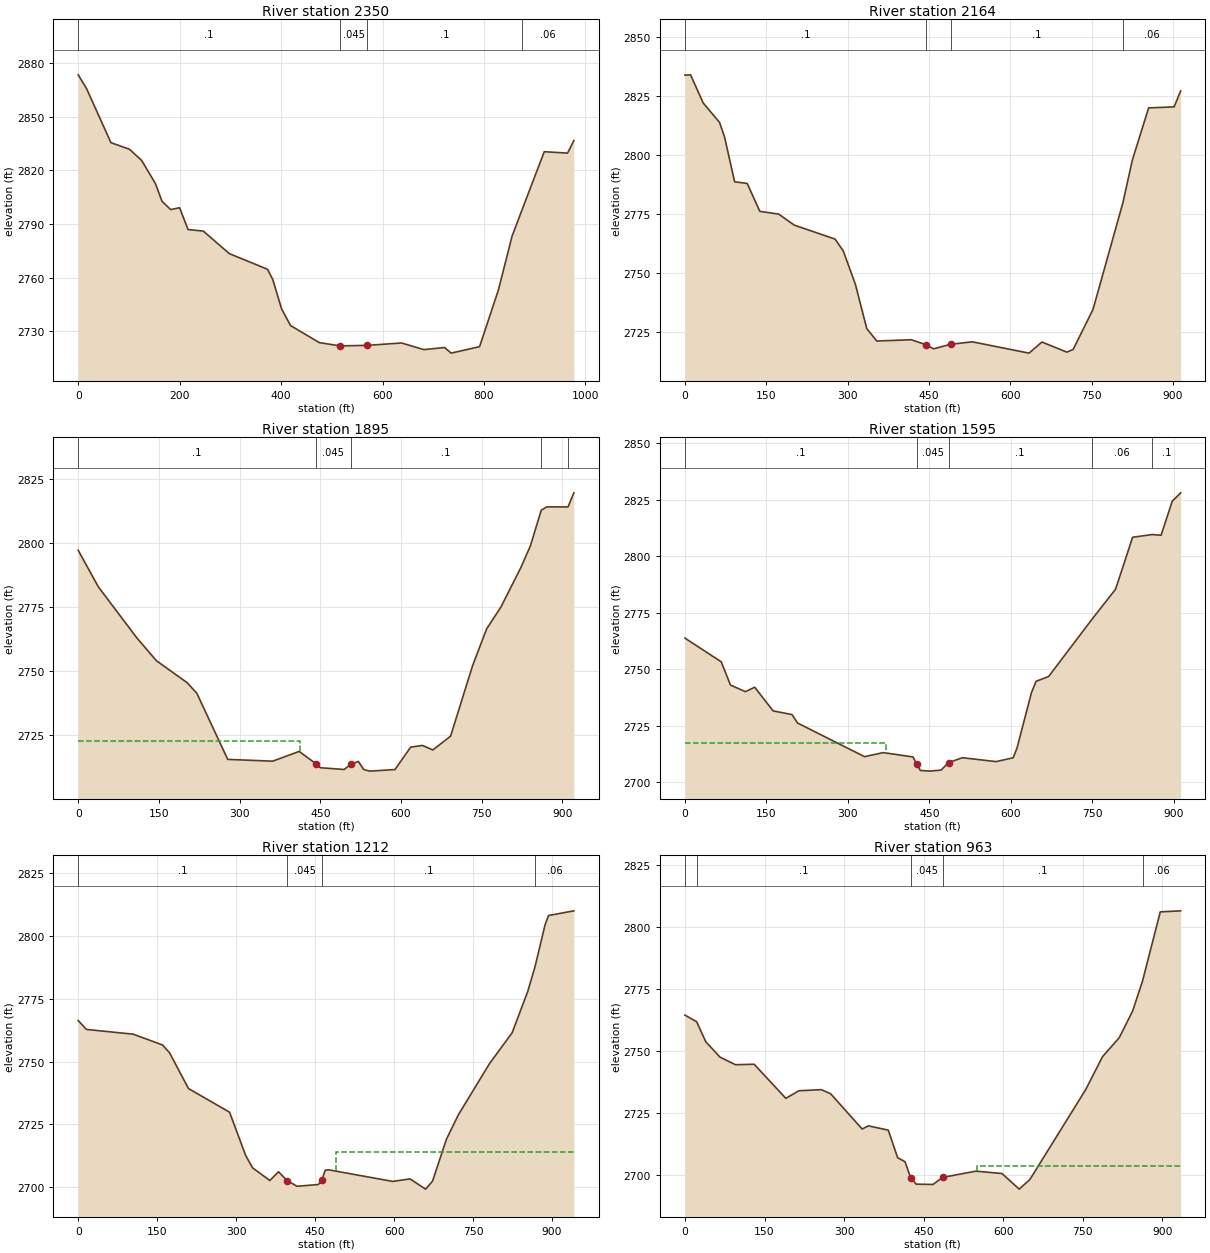
Type RM Length L Ch R = 1 ,2350    ,186.5,186.5,186.5
XS GIS Cut Line= 2
2077142.85997138371766.9720295692076394.86995645372395.830475542
#Sta/Elev= 30
       0 2873.31    16.4 2865.68    64.6  2835.4   100.9 2831.77   125.2 2825.45
   152.3 2812.53   165.2 2802.67   182.3 2798.03   199.9 2799.06   216.6 2786.88
   246.6 2786.02     298 2773.42   373.3 2764.68   383.5 2759.03   400.9 2742.61
   418.6 2733.27   475.2 2723.73     516 2721.89   569.9 2722.17   637.4 2723.51
   681.4 2719.81   722.4 2720.97   735.2 2717.84   791.3 2721.46   828.4 2753.08
   855.2 2783.04  874.58 2797.57   918.8 2830.37   964.7 2829.58   977.2 2836.58
#Mann= 4 ,-1 , 0
       0      .1       0     516    .045       0   569.9      .1       0
  874.58     .06       0
Bank Sta=516,569.9
XS Rating Curve= 0 ,0
Exp/Cntr=0.3,0.1

Type RM Length L Ch R = 1 ,2164    ,269.3,269.3,269.3
XS GIS Cut Line= 2
      2076938.08      371664.743     2076276.082      372295.097
#Sta/Elev= 30
       0 2833.93    10.4 2834.05    33.6 2822.15    63.8  2813.9    73.1 2807.68
    91.6 2788.75   114.8 2788.05   138.1 2776.23   172.9 2775.06   201.6  2770.4
   276.9 2764.48     292 2759.45   314.4 2745.28   335.3 2726.57   353.8 2721.32
   417.3 2721.86   444.2 2719.79   458.5 2718.01   489.8 2719.93   529.9 2720.98
   634.6 2716.19   658.3 2720.89   704.3 2716.61   715.9 2717.76   752.5 2734.68
  807.79 2780.01   824.9 2797.81   855.1 2820.05     902 2820.47   914.1 2827.21
#Mann= 4 ,-1 , 0
       0      .1       0   444.2    .045       0   489.8      .1       0
  807.79     .06       0
Bank Sta=444.2,489.8
XS Rating Curve= 0 ,0
Exp/Cntr=0.3,0.1

Type RM Length L Ch R = 1 ,1895    ,300,300,300
XS GIS Cut Line= 3
     2076596.185      371385.612     2076412.724      371799.241
     2076190.677      372212.341
#Sta/Elev= 30
       0  2797.3    37.5 2783.01   109.3 2763.02   145.4 2754.17   202.6 2745.57
   220.6 2741.43     278 2715.62   361.4 2714.92   410.8 2718.73   442.1 2713.89
   450.3 2712.35   494.6 2711.68   506.7 2713.69   520.9 2714.82   530.9 2711.64
   542.5 2711.03     589 2711.66   618.1  2720.4   639.9 2721.07   659.3 2719.31
   692.3 2724.69   733.3 2752.29   759.3  2766.6   785.9 2775.15   822.7 2790.44
   840.5 2798.95  860.91 2812.98   871.1 2814.26  910.58 2814.25   921.5 2819.75
#Mann= 5 ,-1 , 0
       0      .1       0   442.1    .045       0   506.7      .1       0
  860.91     .06       0  910.58      .1       0
#XS Ineff= 2 , 0
          412.42 2722.87
Permanent Ineff=
       F       F
Bank Sta=442.1,506.7
XS Rating Curve= 0 ,0
Exp/Cntr=0.3,0.1

Type RM Length L Ch R = 1 ,1595    ,382.7,382.7,382.7
XS GIS Cut Line= 3
     2076270.118      371257.597     2076137.411      371693.627
     2075980.531      372123.027
#Sta/Elev= 30
       0 2763.82    66.8 2753.34    83.9 2743.04   111.4 2740.13   128.5 2742.09
   162.4 2731.61   197.1 2729.99   207.4 2726.24   330.8 2711.35   365.1 2713.15
     420 2711.23   426.9 2708.05   433.6 2705.26   450.9 2704.95   471.7 2705.41
   485.6 2708.75   511.1 2710.89     573 2709.16   604.5 2710.86   611.5 2715.12
   638.1 2739.64   646.7 2744.71   669.8 2746.84  749.34 2772.07   793.1 2785.48
   824.5 2808.47  860.75 2809.67   876.9 2809.34   897.4 2824.39   912.9 2828.13
#Mann= 5 ,-1 , 0
       0      .1       0   426.9    .045       0   485.6      .1       0
  749.34     .06       0  860.75      .1       0
#XS Ineff= 2 , 0
          370.82 2717.52
Permanent Ineff=
       F       F
Bank Sta=426.9,485.6
XS Rating Curve= 0 ,0
Exp/Cntr=0.3,0.1

Type RM Length L Ch R = 1 ,1212    ,248.7,248.7,248.7
XS GIS Cut Line= 2
2075775.83107652371135.3110622592075834.20359234372074.966194855
#Sta/Elev= 30
       0 2766.35    15.6  2762.8   104.4  2760.9   160.2  2756.6   173.4 2753.52
   209.5 2739.21   287.5 2729.79     318 2712.59   331.2  2707.6     364 2702.56
   380.5 2706.04   396.9 2702.53   415.7 2700.25   456.1 2700.94   462.7 2702.71
   469.2 2706.62   475.3 2706.82   597.4 2702.19   630.3 2703.19   659.9 2699.11
     673 2702.28   699.3 2718.94   722.3 2728.83   781.5 2749.24   824.2 2761.45
     854 2778.01     868 2788.04   886.7 2804.48   893.3 2808.22   941.5 2810.09
#Mann= 4 ,-1 , 0
       0      .1       0   396.9    .045       0   462.7      .1       0
     868     .06       0
#XS Ineff= 2 , 0
                          490.17         2713.84
Permanent Ineff=
       F       F
Bank Sta=396.9,462.7
XS Rating Curve= 0 ,0
Exp/Cntr=0.3,0.1

Type RM Length L Ch R = 1 ,963     ,268.6,268.6,268.6
XS GIS Cut Line= 2
      2075412.53      371212.699     2075746.241      372085.709
#Sta/Elev= 30
       0 2764.55   22.04 2761.89    39.2 2753.82    66.1 2747.58    95.4  2744.5
   130.5 2744.71   190.2 2730.93   214.8 2733.99     257 2734.44   274.5 2732.82
   334.2 2718.52   345.7 2719.82   383.4 2718.08     401 2706.95     415  2705.3
   425.5 2698.84   436.1 2696.26   467.6 2696.13   485.8 2698.99   548.5 2701.51
   597.7 2700.56   630.3 2694.25   650.6  2698.2   755.7 2734.49   787.3 2747.75
   818.9 2755.45   844.2 2766.24  862.82 2778.37   896.2 2806.25   934.6 2806.68
#Mann= 5 ,-1 , 0
       0     .06       0   22.04      .1       0   425.5    .045       0
   485.8      .1       0  862.82     .06       0
#XS Ineff= 2 , 0
                          550.54          2703.7
Permanent Ineff=
       F       F
Bank Sta=425.5,485.8
XS Rating Curve= 0 ,0
Exp/Cntr=0.3,0.1

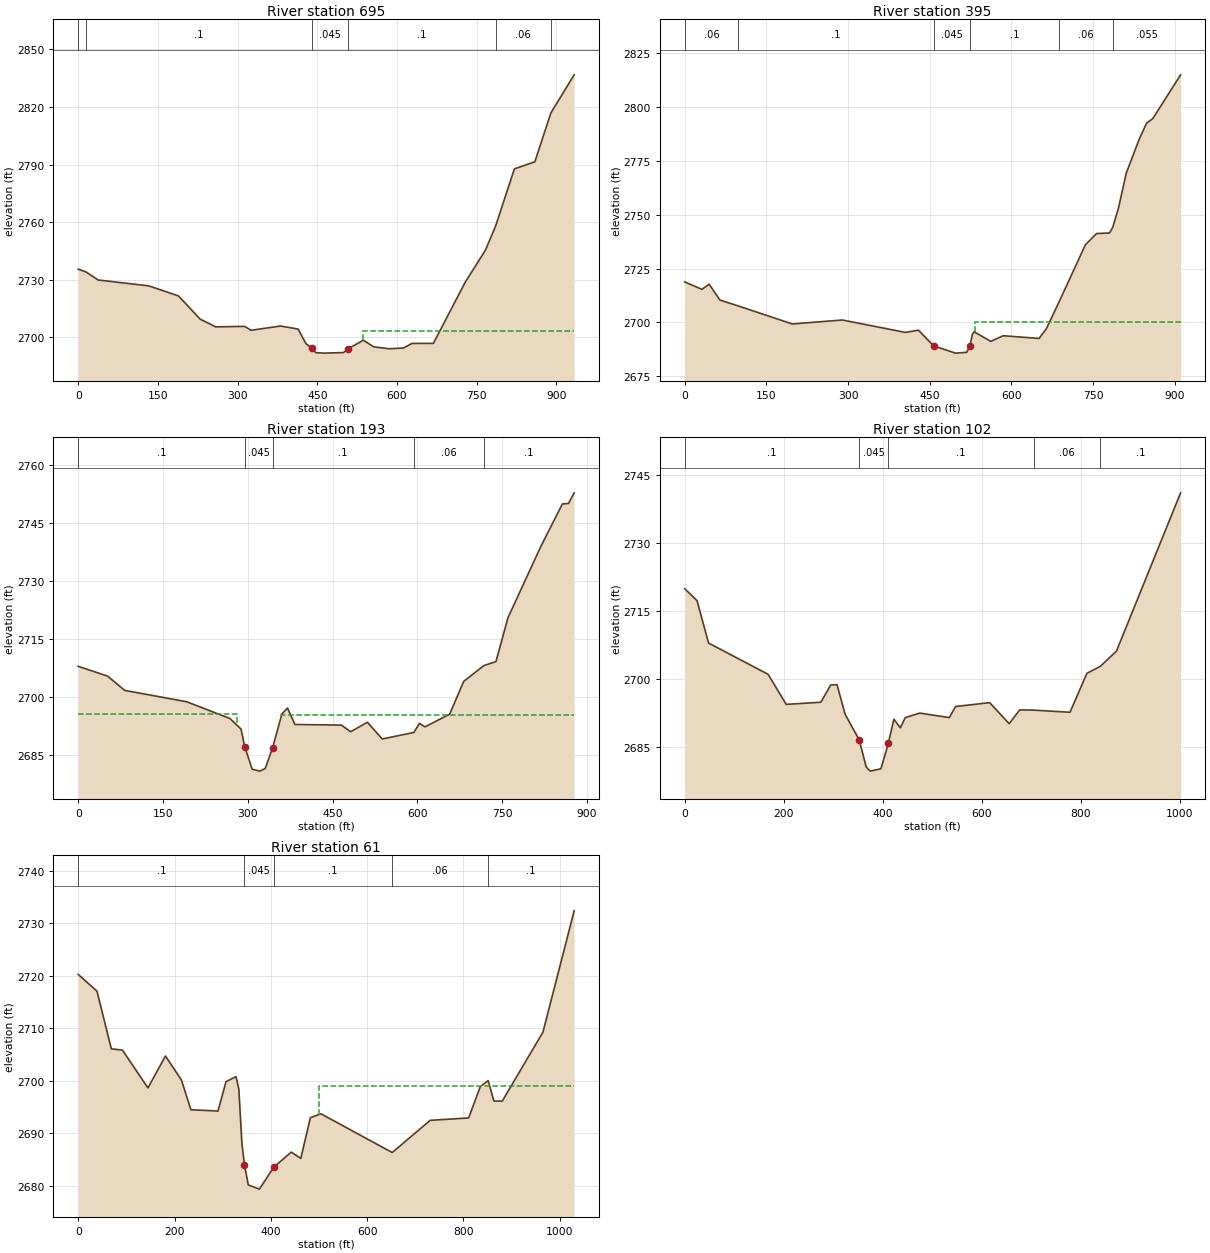
Type RM Length L Ch R = 1 ,695     ,299.3,299.3,299.3
XS GIS Cut Line= 3
     2075148.346      371357.031     2075365.632      371779.442
     2075590.234      372179.095
#Sta/Elev= 30
       0 2735.57    14.7 2734.14    37.5 2729.93   132.9 2726.87   188.8 2721.63
   229.4 2709.58   258.9 2705.51   313.2 2705.78   325.6 2703.73   380.6 2705.96
   413.8 2704.39   428.6 2696.81   440.4 2694.28     447 2692.09   461.8 2691.84
   499.2 2692.13   507.7 2694.05   536.8 2698.56   556.5  2695.1   585.7 2694.11
   612.1  2694.5   628.2 2696.89   668.5 2696.91   728.7 2728.89   766.4  2745.4
  785.67 2758.03     821 2787.79   859.5  2791.5  889.76 2816.97   933.5 2836.79
#Mann= 6 ,-1 , 0
       0    .055       0    14.7      .1       0   440.4    .045       0
   507.7      .1       0  785.67     .06       0  889.76      .1       0
#XS Ineff= 2 , 0
                          536.31         2703.31
Permanent Ineff=
       F       F
Bank Sta=440.4,507.7
XS Rating Curve= 0 ,0
Exp/Cntr=0.3,0.1

Type RM Length L Ch R = 1 ,395     ,183.6,202.2,203.6
XS GIS Cut Line= 2
2074979.29687443371442.9404295912075225.84709023372319.821857487
#Sta/Elev= 30
       0 2718.85    31.7 2715.37      45 2717.77    64.7 2710.41   98.66 2707.66
   197.6 2699.33   289.6 2701.15   405.5 2695.41   429.3 2696.44   457.3 2689.18
   497.2 2685.79     518 2686.17   523.8 2688.88   528.2 2694.31   531.6 2695.69
   562.3 2691.24     585 2693.86   650.9  2692.6   664.5 2697.18  687.93 2709.71
   736.1  2736.1   756.5 2741.26   780.4 2741.53  786.14 2744.07   796.8 2753.11
     811 2769.24   834.9 2785.06   848.5 2792.54   859.7 2794.55   910.9  2814.9
#Mann= 6 ,-1 , 0
       0     .06       0   98.66      .1       0   457.3    .045       0
   523.8      .1       0  687.93     .06       0  786.14    .055       0
#XS Ineff= 2 , 0
                          533.28          2700.4
Permanent Ineff=
       F       F
Bank Sta=457.3,523.8
XS Rating Curve= 0 ,0
Exp/Cntr=0.5,0.3

Type RM Length L Ch R = 1 ,193     ,88.1,91.5,90.7
XS GIS Cut Line= 4
2074990.76792116371527.5917051972074941.80128806371758.022919822
2074920.19836168 372125.272668132075026.77279845372377.306809125
#Sta/Elev= 30
       0 2707.89    51.9 2705.36    82.3 2701.66   191.8 2698.73   268.3 2694.39
     288 2691.66   294.5 2687.09   307.7 2681.27   321.2 2680.78   330.7 2681.46
   343.8  2686.8  360.23 2695.55   370.1 2697.09   383.3 2692.85   465.4 2692.68
   481.9 2690.97   511.5 2693.42   537.7  2689.1   593.6 2690.78   603.5 2693.13
   613.3 2692.23   656.9  2695.5   681.8    2704   717.5 2708.08   738.8 2709.11
   760.2 2720.51   817.2 2738.58   856.2 2749.87   867.1    2750   877.1 2752.76
#Mann= 5 ,-1 , 0
       0      .1       0   294.5    .045       0   343.8      .1       0
   593.6     .06       0   717.5      .1       0
#XS Ineff= 2 , 0
          280.26  2695.5   359.4          2695.2
Permanent Ineff=
       F       F
Bank Sta=294.5,343.8
XS Rating Curve= 0 ,0
Exp/Cntr=0.5,0.3

Type RM Length L Ch R = 1 ,102     ,37.2,40.6,44.6
XS GIS Cut Line= 4
2074908.67680095371428.2182438912074861.15036294371680.252384886
2074855.38958257372080.6266202962074992.20811625372397.469540405
#Sta/Elev= 30
       0 2719.82    24.9  2717.2    48.3 2707.84   168.5 2700.94   205.2 2694.31
   275.1 2694.78     295 2698.59   307.8 2698.65   324.2 2692.12   352.6 2686.48
   366.9 2680.47   374.9 2679.59   396.4  2680.1   410.8 2685.41   411.5 2685.78
   422.7 2691.04   435.8 2689.15   445.6 2691.39   475.2 2692.39   534.7 2691.39
   547.3 2693.84   616.2 2694.69   655.6 2690.05   676.9 2693.09   705.1 2693.04
   778.5 2692.57   812.7 2701.16   839.8 2702.71   872.3 2706.04    1002 2740.96
#Mann= 5 ,-1 , 0
       0      .1       0   352.6    .045       0   410.8      .1       0
   705.1     .06       0   839.8      .1       0
Bank Sta=352.6,411.5
XS Rating Curve= 0 ,0
Exp/Cntr=0.5,0.3

Type RM Length L Ch R = 1 ,61      ,61,61,61
XS GIS Cut Line= 3
2074866.80019766371417.2968812022074796.60176895371974.306152469
2074962.94152393372412.283305492
#Sta/Elev= 30
       0 2720.25      39 2717.05    68.8 2706.07    91.9 2705.83   144.8 2698.63
   181.2 2704.71   214.3 2700.15   234.1 2694.47   290.3 2694.22   306.9 2699.82
   327.7 2700.78   333.6  2698.4   339.9 2688.12   345.3 2683.98   353.2 2680.15
   376.3 2679.35   406.1 2683.53   442.4  2686.4   462.3 2685.21   482.1 2692.95
   503.9 2693.71  652.02 2686.32   730.9 2692.45   810.7 2692.91   835.2 2698.91
  851.35 2700.01   863.3 2696.13   880.6 2696.12   965.1 2709.25  1029.9 2732.36
#Mann= 5 ,-1 , 0
       0      .1       0   345.3    .045       0   406.1      .1       0
  652.02     .06       0  851.35      .1       0
#XS Ineff= 2 , 0
                          499.35         2698.92
Permanent Ineff=
       F       F
Bank Sta=345.3,406.1
XS Rating Curve= 0 ,0
Exp/Cntr=0.3,0.1
LCMann Table=0

Chan Stop Cuts=-1
Use User Specified Reach Order=0
Composite Channel Slope=5